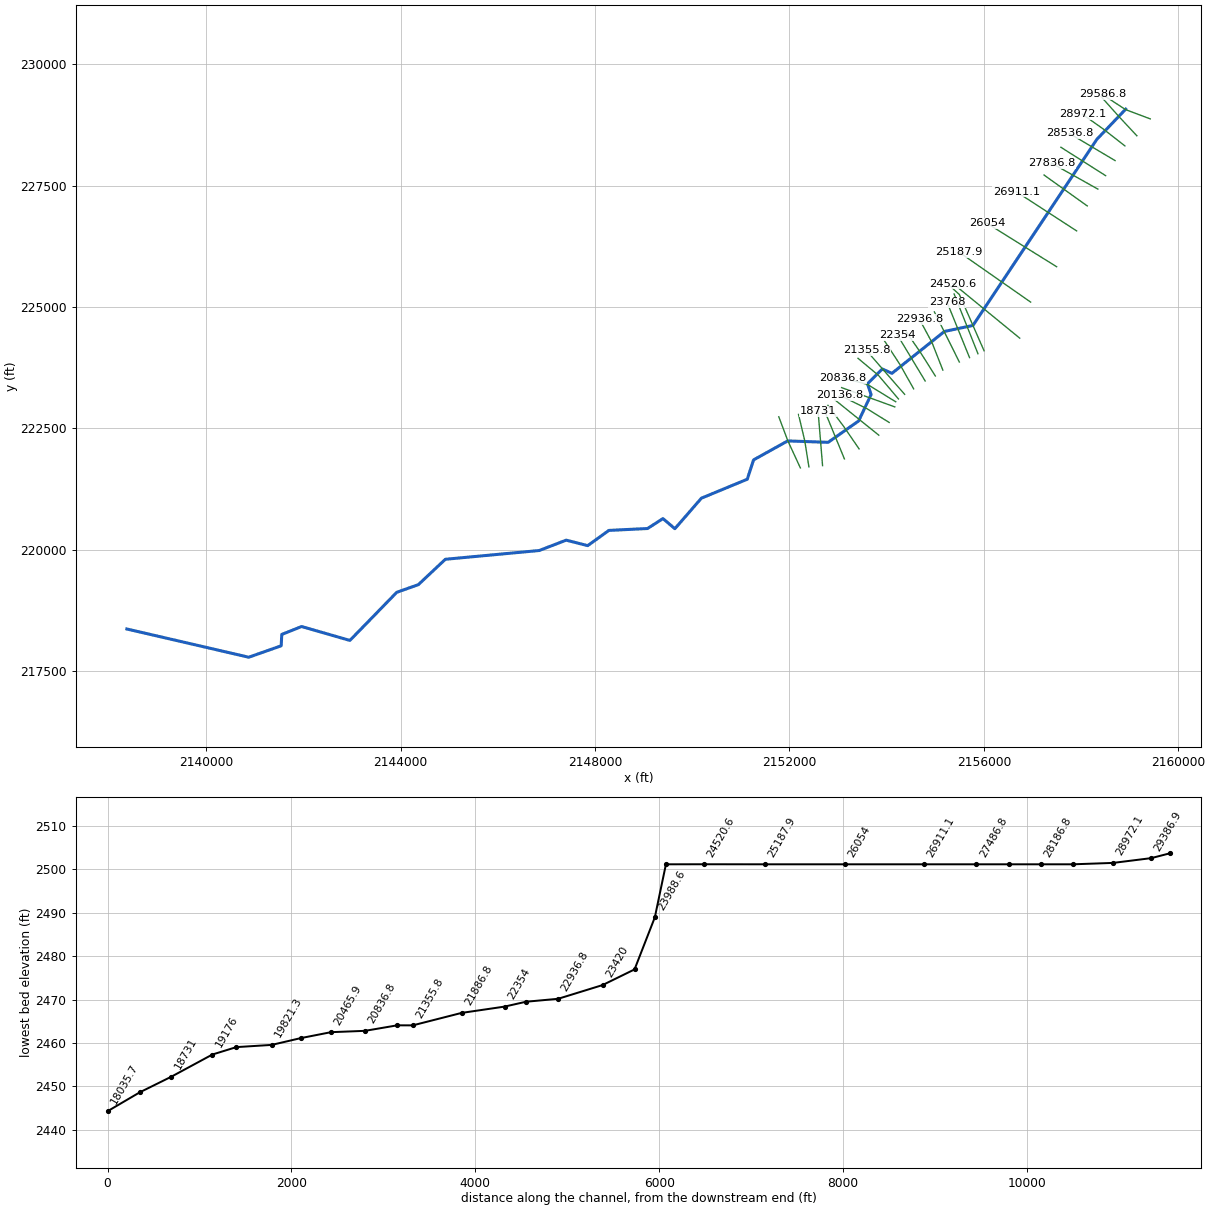
--- DEVILCK.prj (project) ---

Proj Title=DEVILCK
Current Plan=p01
Default Exp/Contr=0,0
English Units
Geom File=g01
Flow File=f01
Plan File=p01
BEGIN DESCRIPTION:
END DESCRIPTION:
DSS Export Rating Curves= 0
DSS Export Rating Curve Sorted= 0
DSS Export Volume Flow Curves= 0
DXF OffsetX= 0
DXF OffsetY= 0
DXF ScaleX= 0
DXF ScaleY= 0

--- DEVILCK.p01 (plan) ---

Plan Title=Floodplain
Program Version=4.00
Geom File=g01
Flow File=f01
K Sum by GR=0
Std Step Tol=0.01
Critical Tol=0.01
Num of Std Step Trials=20
Max Error Tol=0.3
Flow Tol Ratio=0.001
Split Flow NTrial=30
Split Flow Tol=0.02
Split Flow Ratio=0.02
Log Output Level=0
Friction Slope Method=1
Unsteady Friction Slope Method=2
Unsteady Bridges Friction Slope Method=1
Global Log Level=0
CheckData=False
Run HTab=0
Run UNet=0
Run PostProcess=0
UNET Theta=0
UNET Theta Warmup=0
UNET ZTol=0
UNET ZSATol=0
UNET MxIter=0
UNET MaxInSteps=0
UNET DtIC=0
UNET DtMin=0
UNET MaxCRTS=0
UNET WFStab=0
UNET SFStab=0
UNET WFX=0
UNET SFX=0
UNET DSS MLevel=0
UNET DZMax Abort=0
UNET Convert EG Bridges=0
UNET Use Existing IB Tables=0
UNET Froude Limit=0
UNET Froude Power=0
Write IC File=0
Echo Input=False
Echo Output=False
Write Detailed=0

--- DEVILCK.f01 (steady flow) ---

Flow Title=2010 USGS WV Regression Equation
Program Version=4.00
Number of Profiles=1
Profile Names=P100yr
River Rch & RM=DEVILCK,Main      ,29586.8
537.2149
River Rch & RM=DEVILCK,Main      ,28972.1
539.3451
River Rch & RM=DEVILCK,Main      ,28186.8
597.8212
River Rch & RM=DEVILCK,Main      ,27836.8
629.9500
River Rch & RM=DEVILCK,Main      ,26054
685.8411
River Rch & RM=DEVILCK,Main      ,24520.6
830.1149
River Rch & RM=DEVILCK,Main      ,24520.6
748.5392
River Rch & RM=DEVILCK,Main      ,23420
862.6508
River Rch & RM=DEVILCK,Main      ,20836.8
927.5962
River Rch & RM=DEVILCK,Main      ,18731
1030.329
River Rch & RM=DEVILCK,Main      ,15840
1082.582
River Rch & RM=DEVILCK,Main      ,11721.1
1199.593
River Rch & RM=DEVILCK,Main      ,5995.3
1299.395
River Rch & RM=DEVILCK,Main      ,5415.4
1849.036
River Rch & RM=DEVILCK,Main      ,438.8
1943.616
River Rch & RM=DEVILCK,Main      ,438.8
1942.870
Boundary for River Rch & Prof#=DEVILCK,Main      ,1
Up Type=0
Dn Type=3
Dn Slope=0.00406

--- DEVILCK.g01 (geometry) ---

Geom Title=LiDAR
Program Version=4.10

River Reach=DEVILCK         ,Main
Reach XY= 30
     2158919.808      229079.377      2158325.19      228456.764
     2155776.796       224622.78     2155189.734        224498.9
     2154109.873      223636.052      2153910.22      223725.462
     2153605.533      223420.775     2153680.186      223198.553
     2153424.109      222654.282     2152797.373      222214.178
     2151964.301      222243.114     2151261.566      221851.548
      2151132.66      221453.761     2150188.649      221063.136
     2149643.076      220434.229     2149396.983      220642.563
     2149080.576      220438.136     2148285.004      220399.073
     2147848.806      220085.271     2147406.097      220198.552
      2146851.41      219985.011     2144919.769      219804.238
     2144364.213      219281.235      2143920.42        219123.9
     2142955.793      218132.146      2141961.87      218418.605
     2141553.884      218255.844     2141541.948      218021.469
      2140874.63      217786.009     2138365.757      218367.823

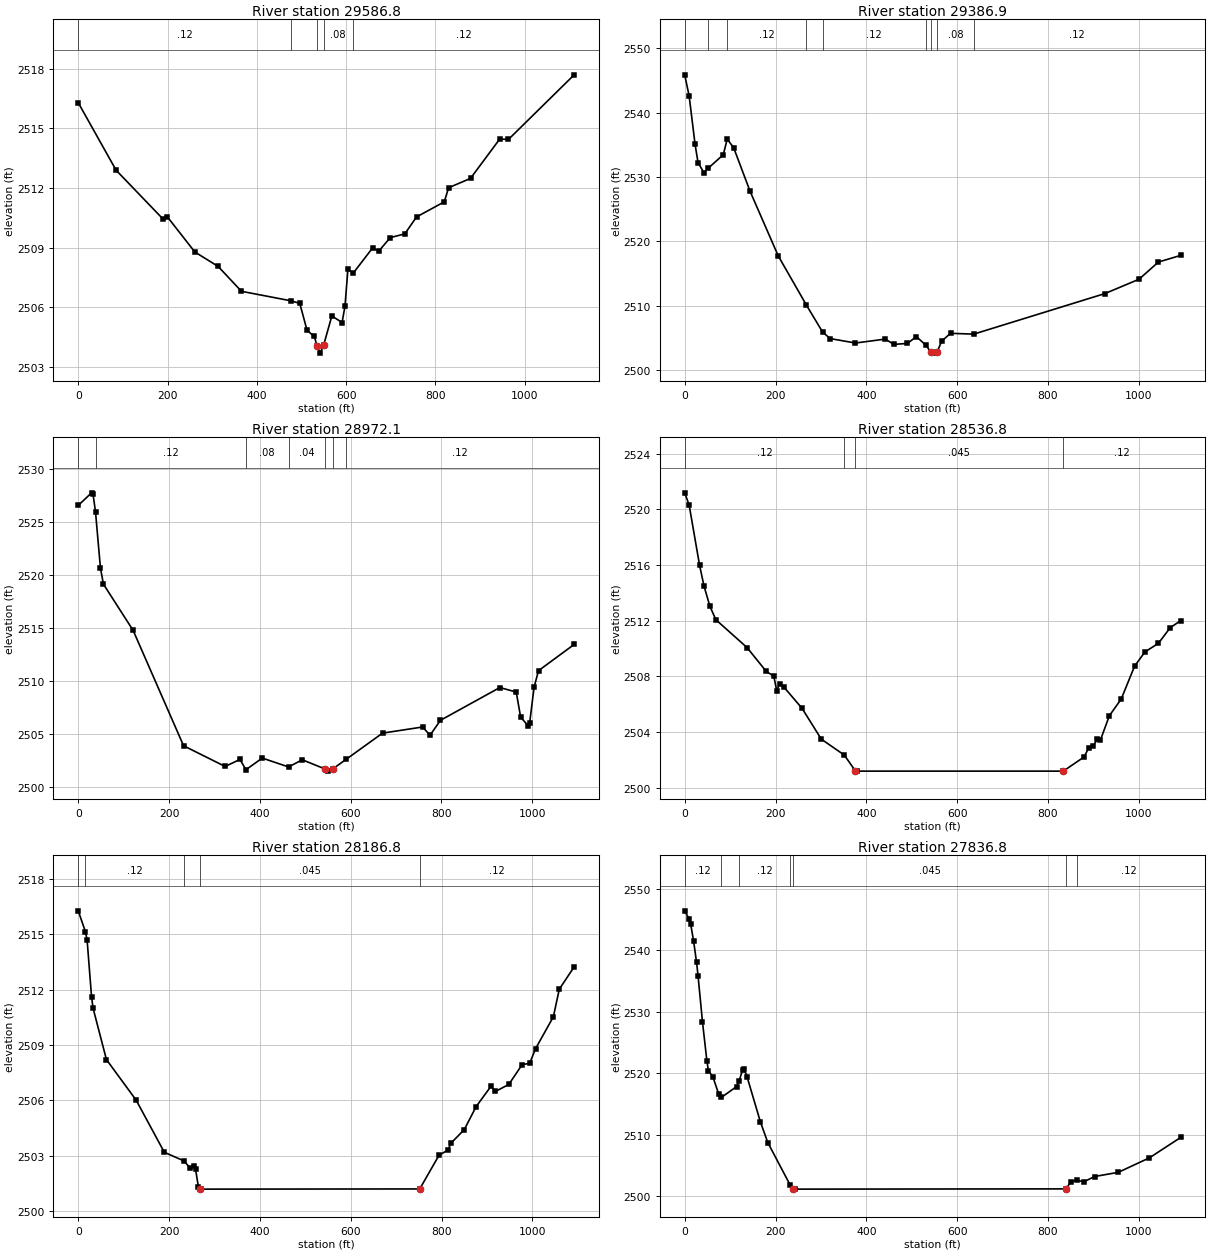
Type RM Length L Ch R = 1 ,29586.8 ,210.6,199.9,193.9
XS GIS Cut Line= 3
     2159423.783      228879.018     2158916.646       229069.89
     2158440.884      229381.533
#Sta/Elev= 30
       0 2516.29    84.9 2512.89   189.3 2510.45   199.1 2510.56   261.1 2508.78
   313.4 2508.05   365.6  2506.8  477.052506.319   496.2 2506.19   512.5 2504.83
   528.8 2504.53   534.4 2504.07   541.9 2503.69   549.4 2504.08     568 2505.56
   590.9 2505.23   597.4 2506.05     604 2507.92  615.39  2507.7   659.5 2508.99
   672.6 2508.81   698.8  2509.5   731.4 2509.69   757.6 2510.54   819.7  2511.3
   829.5 2512.01   878.5 2512.48   943.9 2514.46   963.5 2514.44  1110.6 2517.69
#Mann= 5 ,-1 , 0
       0     .12       0  477.05     .08       0   534.4    .045       0
   549.4     .08       0  615.39     .12       0
Bank Sta=534.4,549.4
XS Rating Curve= 0 ,0
Exp/Cntr=0.3,0.1

Type RM Length L Ch R = 1 ,29386.9 ,410,414.8,420.1
XS GIS Cut Line= 3
     2159148.547      228531.086     2158776.275      228930.699
     2158412.649      229337.963
#Sta/Elev= 30
       0 2545.87     9.8  2542.6    22.9 2535.05    29.4 2532.23    42.5 2530.63
   51.612531.337      85 2533.45   93.632535.876   107.9 2534.53   143.9 2527.78
     206 2517.72  268.242510.047  303.852505.859   320.5 2504.86   376.1 2504.17
   441.5 2504.78   461.1 2503.96   490.6 2504.11   510.2 2505.17  531.432503.816
  541.672502.797   549.4  2502.6     556 2502.78   565.8 2504.46   585.4 2505.68
   636.52505.554   925.4 2511.86  1000.6 2514.09  1043.1 2516.76  1092.1 2517.79
#Mann= 9 ,-1 , 0
       0     .12       0   51.61    .016       0   93.63     .12       0
  268.24    .016       0  303.85     .12       0  531.43     .08       0
  541.67    .045       0     556     .08       0   636.5     .12       0
Bank Sta=541.67,556
XS Rating Curve= 0 ,0
Exp/Cntr=0.3,0.1

Type RM Length L Ch R = 1 ,28972.1 ,432.4,435.3,437.1
XS GIS Cut Line= 3
     2158903.182      228321.521     2158473.629      228658.445
     2158028.333      228975.297
#Sta/Elev= 30
       0 2526.54    29.4 2527.73    32.7 2527.59   38.152525.916      49 2520.62
    55.6 2519.12     121 2514.76   232.1 2503.89   323.6 2501.94   356.3  2502.6
  369.412501.631   405.4 2502.73  463.352501.895   493.6 2502.57   542.6 2501.72
   549.2  2501.5  561.122501.721  590.452502.621   670.3 2505.08   758.6 2505.66
     775 2504.88   797.9 2506.29   928.8 2509.38   964.8 2508.95   974.6 2506.58
     991 2505.78   994.3    2506  1004.1  2509.4  1013.9 2510.97  1092.4 2513.44
#Mann= 7 ,-1 , 0
       0    .016       0   38.15     .12       0  369.41     .08       0
  463.35     .04       0   542.6    .045       0  561.12     .04       0
  590.45     .12       0
Bank Sta=542.6,561.12
XS Rating Curve= 0 ,0
Exp/Cntr=0.3,0.1

Type RM Length L Ch R = 1 ,28536.8 ,350.7,350,349.3
XS GIS Cut Line= 3
     2158700.485      228019.606     2158231.178      228298.653
     2157761.871        228577.7
#Sta/Elev= 30
       0 2521.18     9.8 2520.31    32.7 2515.99    42.5 2514.49    55.6 2513.02
    68.7 2512.06   137.3 2510.06   179.8 2508.34   196.2 2508.01   202.7 2506.96
   209.2 2507.46     219  2507.2   258.3  2505.7   300.8 2503.48  351.452502.335
     376 2501.19   379.3 2501.18   833.7 2501.18   879.5  2502.2   889.3 2502.83
   899.1 2502.97   908.9  2503.5   915.4 2503.41   935.1 2505.16   961.2 2506.36
   990.6 2508.72  1013.5 2509.75    1043 2510.36  1069.1 2511.49    1092 2511.99
#Mann= 4 ,-1 , 0
       0     .12       0  351.45    .016       0     376    .045       0
   833.7     .12       0
Bank Sta=376,833.7
XS Rating Curve= 0 ,0
Exp/Cntr=0.3,0.1

Type RM Length L Ch R = 1 ,28186.8 ,348.8,350,351.2
XS GIS Cut Line= 3
     2158507.252      227708.667     2158046.389       228001.45
     2157585.527      228294.233
#Sta/Elev= 30
       0 2516.28   15.912515.144    19.6 2514.69    29.4 2511.61    32.7    2511
    62.1 2508.21   127.5 2506.01   189.6 2503.18  233.622502.702   245.2 2502.35
     255 2502.43   258.3 2502.27   264.8 2501.28   268.1 2501.19   271.4 2501.18
     752 2501.19   794.5 2503.02   814.1  2503.3   820.6 2503.67   850.1 2504.41
   876.2 2505.66   908.9 2506.76   918.7 2506.48   948.1 2506.86   977.6 2507.94
   993.9    2508    1007  2508.8  1046.2 2510.53  1059.3 2512.03    1092 2513.24
#Mann= 5 ,-1 , 0
       0    .016       0   15.91     .12       0  233.62     .04       0
   268.1    .045       0     752     .12       0
Bank Sta=268.1,752
XS Rating Curve= 0 ,0
Exp/Cntr=0.3,0.1

Type RM Length L Ch R = 1 ,27836.8 ,352.5,350,347.5
XS GIS Cut Line= 3
     2158346.037       227432.35     2157869.801      227699.399
     2157393.564      227966.447
#Sta/Elev= 30
       0 2546.45     9.8 2545.13    13.1 2544.33    19.6 2541.56    26.2 2538.05
    29.4 2535.91    39.2 2528.38      49 2521.97    52.3 2520.44    62.1 2519.45
    75.2 2516.58   80.892516.098   114.4 2517.87  120.092518.836   127.5 2520.58
   130.8 2520.78   137.3 2519.47   166.7 2512.12   183.1 2508.74   232.1 2501.87
   238.7  2501.2   241.9 2501.18   840.2 2501.22   850.1 2502.39  863.442502.601
   879.5 2502.39   902.4 2503.23   954.7 2503.91  1023.3 2506.27    1092 2509.58
#Mann= 7 ,-1 , 0
       0     .12       0   80.89    .016       0  120.09     .12       0
   232.1     .04       0   238.7    .045       0   840.2     .04       0
  863.44     .12       0
Bank Sta=238.7,840.2
XS Rating Curve= 0 ,0
Exp/Cntr=0.3,0.1

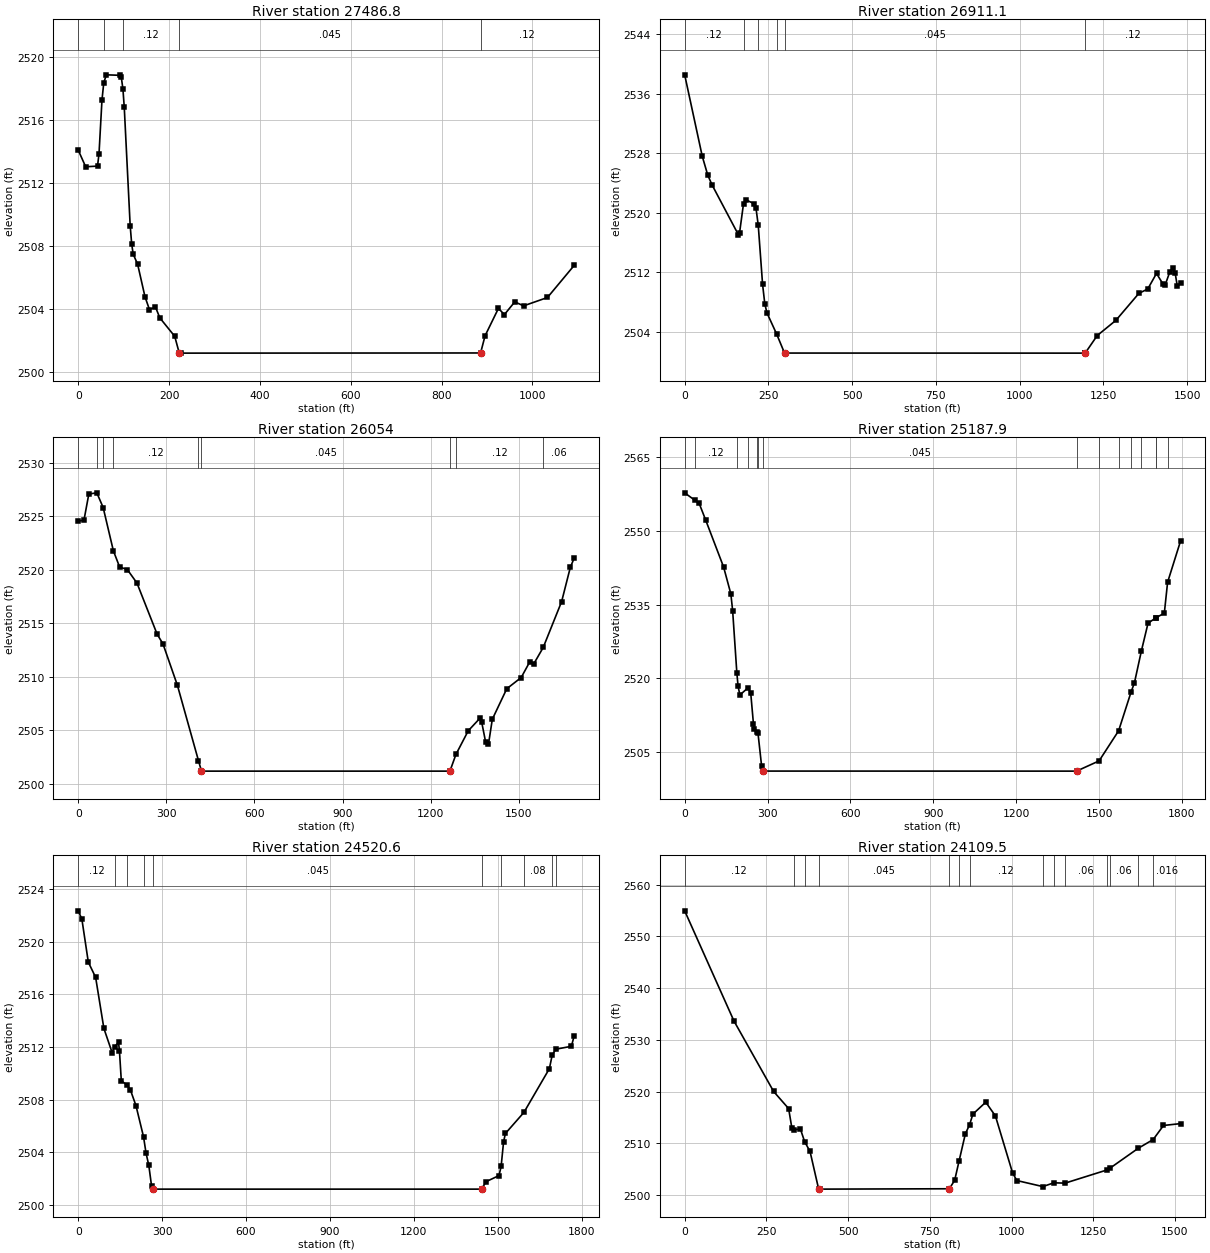
Type RM Length L Ch R = 1 ,27486.8 ,574.7,575.7,576.7
XS GIS Cut Line= 3
     2158127.813      227085.761     2157683.808      227403.529
     2157239.804      227721.297
#Sta/Elev= 30
       0  2514.1    16.4 2513.04    42.5 2513.08    45.8 2513.87    52.3 2517.28
   56.322518.399    62.1 2518.89    91.5 2518.86    94.8 2518.75   98.462517.987
   101.4 2516.82   114.4  2509.3   117.7 2508.14     121 2507.48   130.8 2506.84
   147.1 2504.76   156.9 2503.95     170 2504.12   179.8 2503.42   212.5 2502.25
   222.3  2501.2   225.6 2501.18     886 2501.19   895.8 2502.28   925.3 2504.03
   938.3 2503.63   961.2 2504.44   980.8 2504.19  1033.2 2504.72    1092 2506.76
#Mann= 5 ,-1 , 0
       0     .12       0   56.32    .016       0   98.46     .12       0
   222.3    .045       0     886     .12       0
Bank Sta=222.3,886
XS Rating Curve= 0 ,0
Exp/Cntr=0.3,0.1

Type RM Length L Ch R = 1 ,26911.1 ,856.7,857.1,857.6
XS GIS Cut Line= 2
     2157910.314       226570.09     2156668.995      227377.382
#Sta/Elev= 30
       0 2538.51    52.4  2527.6    68.8 2525.07    81.9 2523.73   160.5 2517.05
   163.8  2517.3  175.68 2521.23   183.4 2521.73   206.4 2521.24   212.9 2520.63
  219.622518.346   232.6  2510.4   239.2 2507.79   245.7 2506.57  274.65 2503.73
   298.1 2501.19 1195.04 2501.18  1195.7 2501.18  1231.8 2503.54  1287.5 2505.58
  1356.2  2509.2  1382.5 2509.78  1408.7 2511.87  1428.3 2510.43  1434.9 2510.37
    1448 2512.02  1457.8 2512.65  1464.4 2511.92  1470.9 2510.13  1480.7 2510.56
#Mann= 6 ,-1 , 0
       0     .12       0  175.68    .016       0  219.62     .12       0
  274.65     .04       0   298.1    .045       0  1195.7     .12       0
Bank Sta=298.1,1195.7
XS Rating Curve= 0 ,0
Exp/Cntr=0.3,0.1

Type RM Length L Ch R = 1 ,26054   ,867.2,866,864.8
XS GIS Cut Line= 2
     2157497.988      225832.243     2156065.696       226726.34
#Sta/Elev= 30
       0 2524.54    19.7 2524.65    36.1 2527.08   63.322527.193   84.932525.819
  119.752521.769     141 2520.26   167.2 2520.02     200 2518.76   268.8 2513.97
   288.5 2513.08   337.7  2509.2  409.282502.173   419.6 2501.18  1265.5 2501.18
 1285.972502.743  1327.8 2504.95  1367.2 2506.11  1373.7 2505.75  1386.8 2503.93
  1396.7 2503.69  1409.8 2506.03    1459 2508.88  1508.1 2509.93  1537.6 2511.41
  1550.8  2511.2  1583.12512.741  1645.8 2517.03  1675.3 2520.22  1688.4 2521.09
#Mann= 9 ,-1 , 0
       0     .12       0   63.32    .016       0   84.93     .08       0
  119.75     .12       0  409.28     .04       0   419.6    .045       0
  1265.5     .04       0 1285.97     .12       0  1583.1     .06       0
Bank Sta=419.6,1265.5
XS Rating Curve= 0 ,0
Exp/Cntr=0.3,0.1

Type RM Length L Ch R = 1 ,25187.9 ,668.9,667.4,665.5
XS GIS Cut Line= 2
     2156964.133      225103.077     2155492.779      226131.722
#Sta/Elev= 30
       0 2557.71   36.942556.195    52.4 2555.57    75.4 2552.27   140.9 2542.64
   167.1 2537.19   173.6  2533.8  188.96 2521.04   193.3 2518.42   199.8 2516.65
  229.342518.104   239.2 2516.98     249 2510.74   252.3 2509.75  262.012509.201
  265.382508.892   278.5  2502.2     285 2501.19  1418.5 2501.18  1500.22503.261
 1570.852509.375 1615.812517.229  1628.2 2519.14 1653.462525.639  1677.3 2531.22
  1705.9 2532.33 1707.062532.372  1736.3 2533.26 1748.172539.545  1795.3 2547.97
#Mann= 15 ,-1 , 0
       0    .016       0   36.94     .12       0  188.96    .016       0
  229.34     .08       0  262.01     .12       0  265.38     .04       0
     285    .045       0  1418.5     .04       0  1500.2     .12       0
 1570.85    .016       0 1615.81     .12       0 1653.46     .06       0
  1705.9     .08       0 1707.06    .016       0 1748.17     .12       0
Bank Sta=285,1418.5
XS Rating Curve= 0 ,0
Exp/Cntr=0.3,0.1

Type RM Length L Ch R = 1 ,24520.6 ,421.9,411.1,400.3
XS GIS Cut Line= 2
     2156738.439      224360.889     2155366.911      225485.021
#Sta/Elev= 30
       0 2522.35    13.1 2521.72    36.1 2518.45    62.3 2517.29    91.8 2513.41
   121.3 2511.57  130.972512.029   144.2 2512.35   147.5 2511.69   154.1 2509.43
  175.152509.091   186.8 2508.72   206.5 2507.54   233.62505.167   242.6 2503.92
   252.4    2503   262.2 2501.44   268.8 2501.19  1442.3 2501.19  1458.7 2501.76
  1504.6 2502.22 1512.242502.911    1521 2504.78  1527.5 2505.42 1593.862507.027
  1684.8 2510.35 1694.992511.389 1708.022511.829  1763.5 2512.05  1773.4 2512.83
#Mann= 10 ,-1 , 0
       0     .12       0  130.97    .016       0  175.15     .12       0
   233.6     .04       0   268.8    .045       0  1442.3     .04       0
 1512.24     .06       0 1593.86     .08       0 1694.99     .12       0
 1708.02     .06       0
Bank Sta=268.8,1442.3
XS Rating Curve= 0 ,0
Exp/Cntr=0.3,0.1

Type RM Length L Ch R = 1 ,24109.5 ,121.6,120.8,120.3
XS GIS Cut Line= 3
     2156004.932      224100.472      2155497.12      225259.327
     2155310.488      225428.597
#Sta/Elev= 30
       0 2554.95   150.8 2533.66   272.1 2520.05     318 2516.74   327.8 2513.03
  333.592512.641     354  2512.8  367.012510.343   383.5 2508.46   409.7 2501.23
     413 2501.18   809.6 2501.25     826 2502.89  839.212506.558   858.8  2511.9
  871.462513.589   881.7 2515.67   921.1 2517.98   950.6 2515.32    1003 2504.34
  1016.1 2502.84 1095.722501.673 1129.44  2502.4  1163.72502.338 1293.032504.905
 1299.922505.172 1387.842509.085 1433.292510.762  1464.8 2513.48  1517.2 2513.84
#Mann= 14 ,-1 , 0
       0     .12       0  333.59    .016       0  367.01     .12       0
   409.7    .045       0   809.6     .12       0  839.21     .06       0
  871.46     .12       0 1095.72     .06       0 1129.44     .04       0
  1163.7     .06       0 1293.03     .12       0 1299.92     .06       0
 1387.84     .12       0 1433.29    .016       0
Bank Sta=409.7,809.6
XS Rating Curve= 0 ,0
Exp/Cntr=0.3,0.1

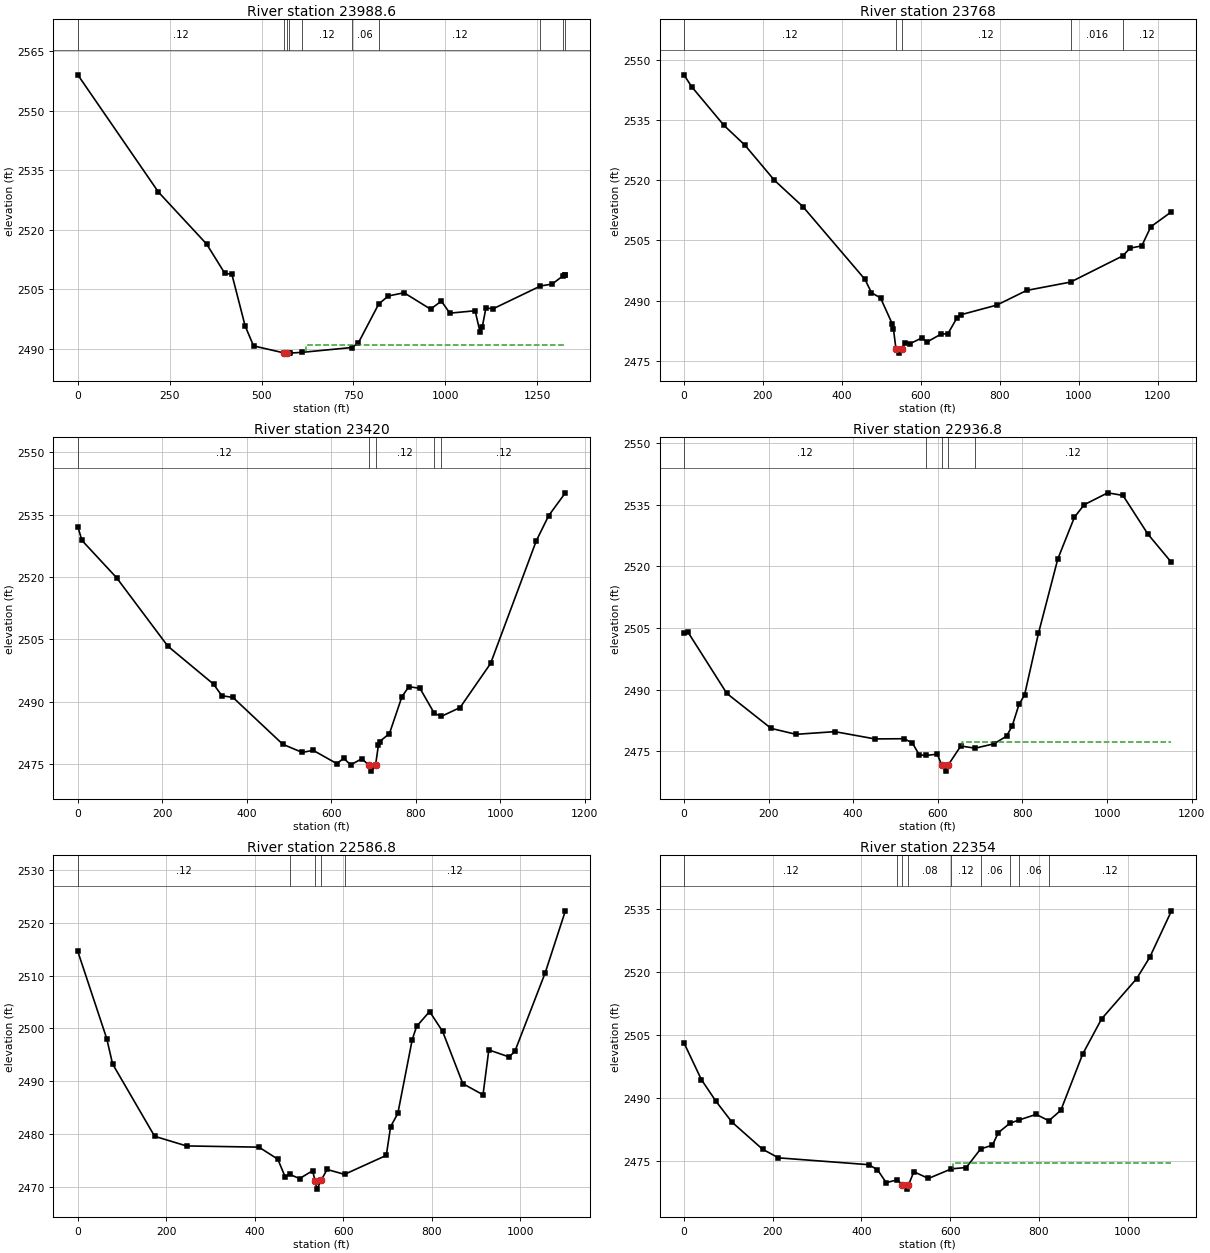
Type RM Length L Ch R = 1 ,23988.6 ,220,220.6,219.4
XS GIS Cut Line= 2
     2155879.064      224039.709     2155388.613      225272.347
#Sta/Elev= 30
       0 2559.02   219.5 2529.49   350.5 2516.42   399.6  2509.1   419.3 2508.77
   455.3  2495.8   478.2 2490.78   560.1 2489.03     570 2489.01  574.762488.976
   576.5 2488.96  609.29 2489.15  745.482490.375   763.2 2491.51  819.022501.367
   845.1 2503.35   887.7 2504.16   959.8 2500.03   989.2 2502.06  1012.2 2499.02
    1081 2499.63  1094.1 2494.38  1100.6 2495.61  1110.4 2500.31  1130.1 2500.13
 1258.842505.859  1290.6 2506.35 1319.672508.385 1324.682508.656  1326.6 2508.74
#Mann= 10 ,-1 , 0
       0     .12       0   560.1    .045       0     570     .12       0
  574.76     .06       0  609.29     .12       0  745.48     .06       0
  819.02     .12       0 1258.84    .016       0 1319.67     .12       0
 1324.68    .016       0
#XS Ineff= 2 , 0
                           621.1         2491.02
Permanent Ineff=
       F       F
Bank Sta=560.1,570
XS Rating Curve= 0 ,0
Exp/Cntr=0.3,0.1

Type RM Length L Ch R = 1 ,23768   ,343.3,348,347.1
XS GIS Cut Line= 2
     2155706.104       223959.63     2155242.562      225103.728
#Sta/Elev= 30
       0 2546.21    19.6 2543.26   101.5 2533.62   153.9 2528.77   229.2 2519.97
   301.2 2513.42   458.4 2495.32   474.8    2492   497.7 2490.71   527.2 2484.32
   530.4 2483.01     537 2477.91   543.5 2476.97   551.7 2477.95   559.9 2479.57
     573 2479.35   602.5 2480.76   615.6 2479.75   651.6 2481.74     668 2481.75
   690.9 2485.67   700.7 2486.51   792.4 2488.93   867.7 2492.57  978.822494.646
 1110.682501.148  1129.7 2503.09  1159.1 2503.65    1182 2508.41  1234.4 2512.14
#Mann= 5 ,-1 , 0
       0     .12       0     537    .045       0   551.7     .12       0
  978.82    .016       0 1110.68     .12       0
Bank Sta=537,551.7
XS Rating Curve= 0 ,0
Exp/Cntr=0.3,0.1

Type RM Length L Ch R = 1 ,23420   ,480.7,483.1,480
XS GIS Cut Line= 2
     2155496.034      223869.353     2154982.146      224902.339
#Sta/Elev= 30
       0 2532.09     9.8 2528.79    91.8 2519.82     213 2503.39   321.2 2494.26
   340.9 2491.47   367.1 2491.07   485.1 2479.81     531 2477.86   557.2 2478.35
   612.9 2475.16   629.3 2476.44   645.7 2474.86   671.9 2476.33  689.43 2474.75
   694.9 2473.36   704.7 2474.86   711.3 2479.57   714.5 2480.47   737.5 2482.39
     767 2491.24   783.4 2493.64   809.6 2493.26  843.882487.209  860.562486.534
   904.6 2488.63   976.8 2499.22  1084.9 2528.68  1114.4 2534.75  1153.8 2540.22
#Mann= 5 ,-1 , 0
       0     .12       0  689.43    .045       0   704.7     .12       0
  843.88    .016       0  860.56     .12       0
Bank Sta=689.43,704.7
XS Rating Curve= 0 ,0
Exp/Cntr=0.3,0.1

Type RM Length L Ch R = 1 ,22936.8 ,342.6,350,351.4
XS GIS Cut Line= 3
     2155156.991      223702.175     2154931.766      224274.496
     2154676.421      224747.029
#Sta/Elev= 30
       0 2503.82     9.8 2503.97   101.4  2489.1   206.1 2480.59     265 2479.15
   356.6  2479.8   451.5 2478.03   520.2 2478.08   539.8 2477.07   556.2 2474.14
  573.182474.023   598.7 2474.33  609.052471.722   618.3  2470.2   624.9 2471.74
   654.3 2476.31  688.232475.774     733 2476.85   762.4 2478.71   775.5 2481.12
   791.9 2486.43     805 2488.73   837.8  2503.7   883.6 2521.81   922.9 2531.96
   945.8 2534.98  1001.5 2537.88  1037.5 2537.25  1096.5 2527.83  1152.2 2520.95
#Mann= 5 ,-1 , 0
       0     .12       0  573.18     .08       0  609.05    .045       0
   624.9     .08       0  688.23     .12       0
#XS Ineff= 2 , 0
                           656.5         2477.32
Permanent Ineff=
       F       F
Bank Sta=609.05,624.9
XS Rating Curve= 0 ,0
Exp/Cntr=0.3,0.1

Type RM Length L Ch R = 1 ,22586.8 ,233.4,232.8,229.9
XS GIS Cut Line= 3
     2155001.876      223581.608      2154712.03      224041.972
     2154396.958      224502.946
#Sta/Elev= 30
       0  2514.6    65.5 2498.04    78.6 2493.26   173.7 2479.54   245.8 2477.71
   409.6 2477.48   452.2  2475.2   468.6 2471.89  479.342472.309   501.4 2471.52
   530.9 2473.01   536.5 2471.07   540.7 2469.52   550.5 2471.24   563.6 2473.25
  603.052472.319   697.5 2475.92   707.3 2481.37   723.6 2483.88   756.2 2497.89
     766 2500.37   795.4  2503.2   824.8 2499.43   870.5 2489.52   916.2 2487.41
   929.3 2495.92     975 2494.59   988.1 2495.62  1056.7 2510.52  1102.4 2522.29
#Mann= 5 ,-1 , 0
       0     .12       0  479.34     .08       0   536.5    .045       0
   550.5     .08       0  603.05     .12       0
Bank Sta=536.5,550.5
XS Rating Curve= 0 ,0
Exp/Cntr=0.3,0.1

Type RM Length L Ch R = 1 ,22354   ,458.1,467.2,444.5
XS GIS Cut Line= 2
     2154792.909      223478.728     2154225.201        224419.7
#Sta/Elev= 30
       0 2503.27    39.4 2494.48    72.2 2489.33   108.3 2484.36   177.2 2477.91
   213.2 2475.85   416.6 2474.22   436.3 2473.02     456 2469.93  481.212470.637
   492.1  2469.4   501.9  2468.4  506.182469.388   518.3 2472.54   551.1 2470.94
  602.992473.228   636.4 2473.55  668.762477.973   695.5 2478.87   708.6 2481.84
  734.542484.072  754.41 2484.83   793.9  2486.2  822.572484.687   849.6 2487.18
   898.8 2500.56   941.5 2508.95  1020.2 2518.49  1049.8 2523.58    1099 2534.68
#Mann= 9 ,-1 , 0
       0     .12       0  481.21     .08       0   492.1    .045       0
  506.18     .08       0  602.99     .12       0  668.76     .06       0
  734.54     .12       0  754.41     .06       0  822.57     .12       0
#XS Ineff= 2 , 0
                          605.64         2474.58
Permanent Ineff=
       F       F
Bank Sta=492.1,506.18
XS Rating Curve= 0 ,0
Exp/Cntr=0.3,0.1

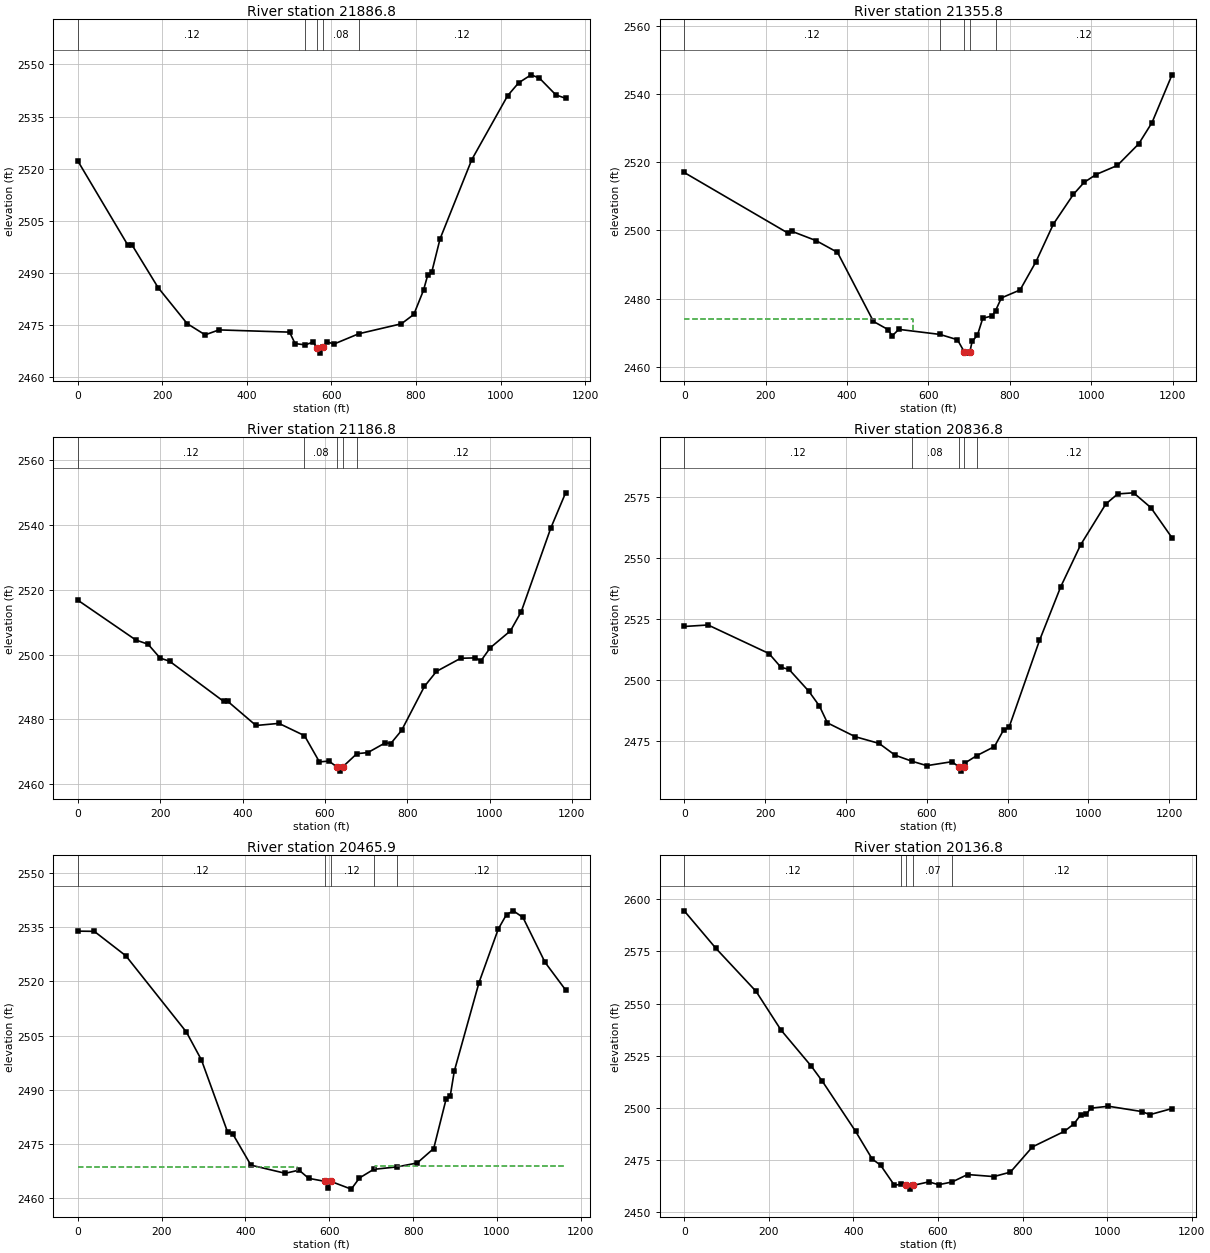
Type RM Length L Ch R = 1 ,21886.8 ,529.7,531.1,524.3
XS GIS Cut Line= 3
     2154555.828       223316.65       2154273.4      223818.734
     2153957.392      224302.247
#Sta/Elev= 30
       0 2522.23   117.8 2498.12   127.6 2498.19   189.8 2485.82   258.6 2475.44
   301.1 2472.21   333.9 2473.63   500.8 2472.99   513.9 2469.69  537.832469.329
   556.4 2470.12   566.2 2468.53   572.8 2466.95   579.3 2468.66   589.1 2470.25
   605.4 2469.54  664.522472.522   765.3 2475.39   794.7 2478.08   817.6 2485.03
   827.4 2489.32   837.1 2490.24   856.7  2499.8   931.8 2522.61  1016.6    2541
  1042.7 2544.71  1072.1    2547  1091.7 2546.06  1130.8 2541.21  1153.7 2540.26
#Mann= 5 ,-1 , 0
       0     .12       0  537.83     .08       0   566.2    .045       0
   579.3     .08       0  664.52     .12       0
Bank Sta=566.2,579.3
XS Rating Curve= 0 ,0
Exp/Cntr=0.3,0.1

Type RM Length L Ch R = 1 ,21355.8 ,181.9,168.9,170.8
XS GIS Cut Line= 2
     2154371.034      223202.686     2153584.576        224107.2
#Sta/Elev= 30
       0 2516.98   255.4  2499.2   265.3 2499.72   324.2 2497.02   376.6 2493.59
     465 2473.36   501.1 2470.96   510.9 2469.12   527.3 2471.04  628.392469.559
   671.4    2468   687.7 2464.55   694.3 2464.08  702.092464.546   707.4 2467.49
   720.5 2469.34   733.6 2474.29   756.5 2474.97  764.992476.523   779.4 2480.25
   825.3 2482.58   864.6 2490.91   907.1 2501.87   956.3 2510.57   982.5 2514.07
  1011.9 2516.38  1064.3 2519.04  1116.7 2525.35  1149.5  2531.6  1198.6 2545.58
#Mann= 5 ,-1 , 0
       0     .12       0  628.39     .08       0   687.7    .045       0
  702.09     .08       0  764.99     .12       0
#XS Ineff= 2 , 0
          562.23 2474.19
Permanent Ineff=
       F       F
Bank Sta=687.7,702.09
XS Rating Curve= 0 ,0
Exp/Cntr=0.3,0.1

Type RM Length L Ch R = 1 ,21186.8 ,327.5,350,359.6
XS GIS Cut Line= 3
     2154242.989      223108.605      2153831.94      223593.917
     2153410.775      223945.558
#Sta/Elev= 30
       0 2516.76     141 2504.48   170.5  2503.2     200 2498.92   222.9 2497.95
   354.1 2485.58   363.9 2485.62   432.7 2478.15   488.5  2478.8  550.532475.018
   586.8 2466.93   609.8 2467.19   628.5 2465.45     636 2464.09   643.5 2465.41
  677.632469.462   704.6 2469.81     747 2472.83   760.1 2472.59   786.2 2476.61
   841.7 2490.17   871.1 2494.82   929.9 2498.86   965.8 2498.98   978.9 2498.05
  1001.8  2502.1  1050.8 2507.32  1076.9 2513.21  1148.7 2538.97  1184.7 2549.83
#Mann= 5 ,-1 , 0
       0     .12       0  550.53     .08       0   628.5    .045       0
   643.5     .08       0  677.63     .12       0
Bank Sta=628.5,643.5
XS Rating Curve= 0 ,0
Exp/Cntr=0.3,0.1

Type RM Length L Ch R = 1 ,20836.8 ,366.6,370.9,353.8
XS GIS Cut Line= 3
     2154186.676      223050.249     2153602.492      223409.044
     2153097.807       223539.89
#Sta/Elev= 30
       0 2521.96      59 2522.57   209.9 2510.88   239.5 2505.24   259.1 2504.45
   308.3 2495.48   334.6 2489.44   354.3 2482.55   423.2 2476.89   482.2 2474.15
   521.6 2469.35  563.142466.883   600.3 2465.06   662.6 2466.68     679 2464.59
   685.6 2462.82   692.1 2464.59   695.4 2466.22  723.462469.115   767.6 2472.86
   790.5 2479.75   803.6 2480.68     879 2516.23   931.5 2538.17   980.7  2555.3
    1043 2572.01  1072.5 2576.15  1111.8  2576.6  1154.5 2570.56  1206.9 2558.22
#Mann= 5 ,-1 , 0
       0     .12       0  563.14     .08       0     679    .045       0
   692.1     .08       0  723.46     .12       0
Bank Sta=679,692.1
XS Rating Curve= 0 ,0
Exp/Cntr=0.3,0.1

Type RM Length L Ch R = 1 ,20465.9 ,332,329.1,321.9
XS GIS Cut Line= 2
     2154167.909      222944.005     2153074.159      223341.575
#Sta/Elev= 30
       0  2533.9    39.3 2533.84   114.7 2527.07     259 2505.99     295 2498.25
   357.3 2478.32   370.4 2477.64     413 2469.15     495 2466.89   527.8 2467.77
   550.7  2465.5  589.352464.662   596.6 2462.83   603.2 2464.67   652.4 2462.51
     672  2465.6  705.822467.979  762.652468.681   809.7 2469.75   849.1 2473.75
   878.6 2487.39   888.4 2488.18   898.2 2495.15   957.2 2519.67  1003.1 2534.47
  1022.8  2538.5  1039.2 2539.52  1062.1 2537.68  1114.6 2525.29  1163.8 2517.62
#Mann= 5 ,-1 , 0
       0     .12       0  589.35    .045       0   603.2     .12       0
  705.82     .08       0  762.65     .12       0
#XS Ineff= 2 , 0
          522.25 2468.77  710.23         2468.88
Permanent Ineff=
       F       F
Bank Sta=589.35,603.2
XS Rating Curve= 0 ,0
Exp/Cntr=0.3,0.1

Type RM Length L Ch R = 1 ,20136.8 ,317.9,315.5,308.6
XS GIS Cut Line= 3
     2154052.241      222623.684     2153599.523      222904.679
     2153043.419      223180.188
#Sta/Elev= 30
       0 2594.48    75.2 2576.45     170 2555.87   228.8 2537.38   300.7    2520
   326.9 2512.75   405.4 2488.77   444.6 2475.52   464.2 2472.65   496.9 2463.02
  513.482463.451  524.412462.908   532.8 2461.14   540.3  2462.9   578.6 2464.62
   601.4 2463.26  633.28 2464.56     670 2468.13   732.1 2467.15   771.3 2469.29
   823.5 2481.39   898.7 2488.81   921.5  2492.4   937.9  2496.8   950.9 2496.92
   960.7 2499.91  1003.2 2500.85  1081.6 2498.32  1101.2 2496.83  1153.4 2499.75
#Mann= 5 ,-1 , 0
       0     .12       0  513.48     .07       0  524.41    .045       0
   540.3     .07       0  633.28     .12       0
Bank Sta=524.41,540.3
XS Rating Curve= 0 ,0
Exp/Cntr=0.3,0.1

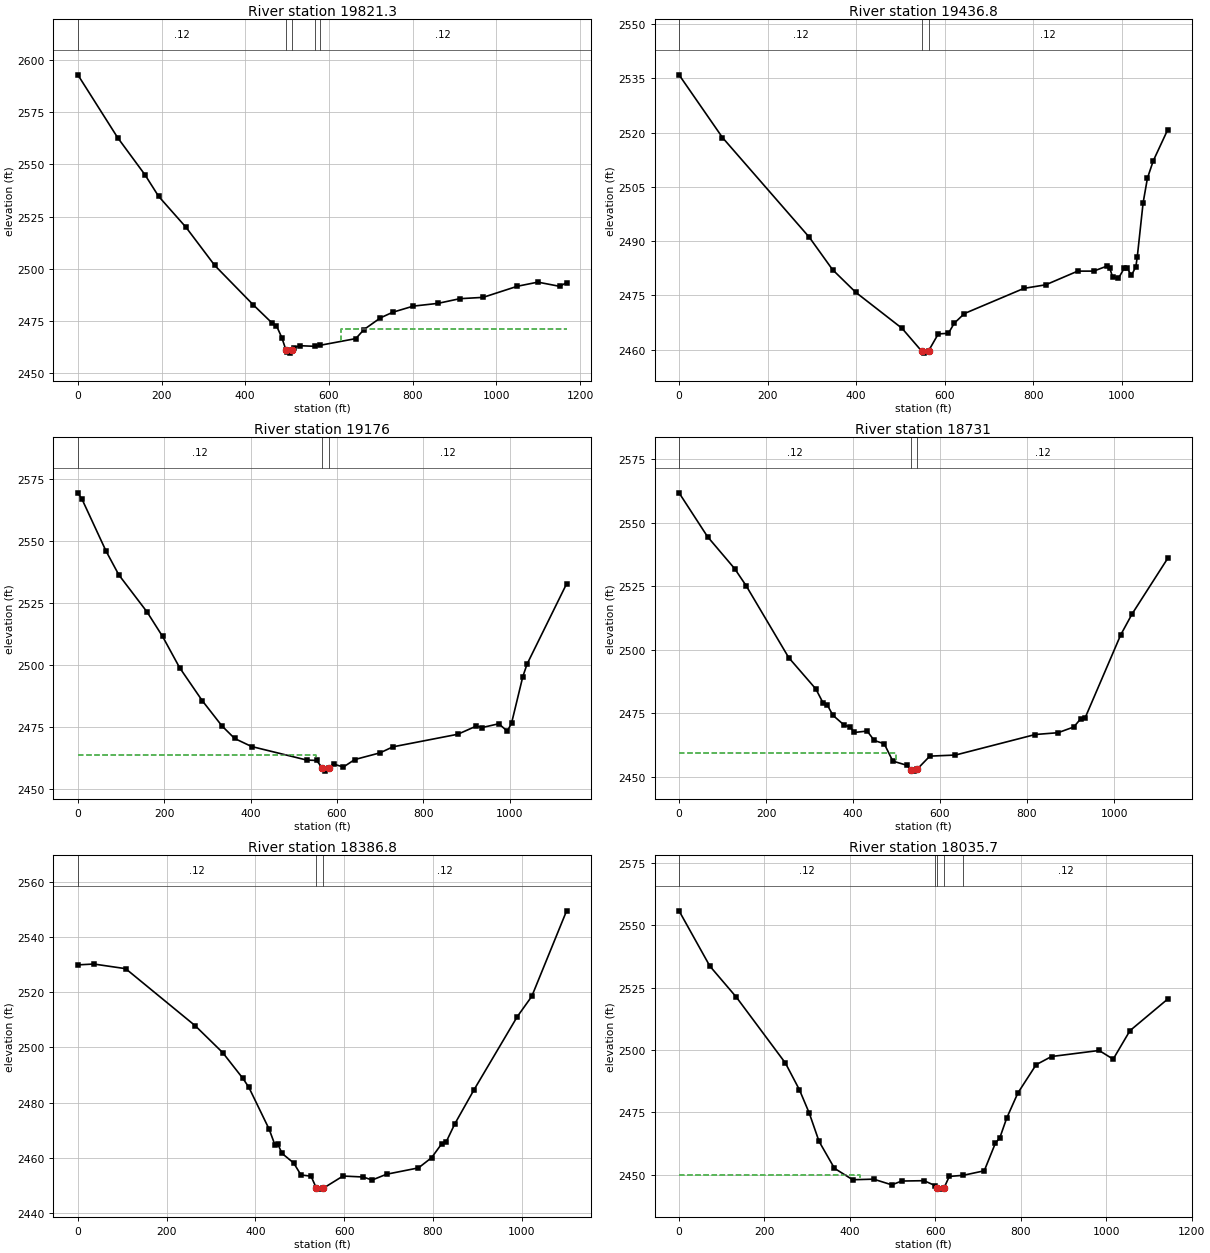
Type RM Length L Ch R = 1 ,19821.3 ,390.7,384.5,377
XS GIS Cut Line= 2
     2153839.784      222360.672     2152930.062      223093.311
#Sta/Elev= 30
       0 2592.98    94.9 2562.93   160.3  2545.1     193 2534.74   258.5 2519.89
   327.2 2501.61   418.8 2482.81   464.6 2473.92   474.4 2472.81   487.5    2467
   497.3 2461.09   500.6 2459.98   507.1 2459.58  512.782461.112     517 2462.22
     530 2463.14  567.11 2462.84  577.892463.295   664.2 2466.54   683.8 2470.88
   723.1 2476.48   752.5 2479.17   801.6 2482.11   860.5 2483.43   912.8 2485.67
   968.5 2486.31  1050.3 2491.63  1099.4 2493.61  1151.7 2491.59  1168.1 2493.39
#Mann= 5 ,-1 , 0
       0     .12       0   497.3    .045       0  512.78     .12       0
  567.11     .06       0  577.89     .12       0
#XS Ineff= 2 , 0
                           629.1         2471.08
Permanent Ineff=
       F       F
Bank Sta=497.3,512.78
XS Rating Curve= 0 ,0
Exp/Cntr=0.3,0.1

Type RM Length L Ch R = 1 ,19436.8 ,265.8,260.8,254.6
XS GIS Cut Line= 3
     2153433.051      222078.802     2153119.175      222537.607
     2152791.256      222976.485
#Sta/Elev= 30
       0 2535.93    98.1  2518.6   294.3 2491.05   346.6 2482.13   398.9 2475.88
   503.6 2465.92   548.4 2459.56   552.6 2459.07   563.4 2459.66   585.4 2464.37
   608.4 2464.55   621.5 2467.33   644.5    2470     779 2476.96   828.2 2477.94
   900.4 2481.72   936.4 2481.72     966 2483.09   972.5 2482.65   979.1 2480.09
   992.2  2479.7  1005.3  2482.5  1011.9  2482.5  1021.7 2480.56  1031.6 2482.92
  1034.9 2485.68    1048 2500.55  1057.8 2507.39  1070.9 2512.16  1103.8 2520.82
#Mann= 3 ,-1 , 0
       0     .12       0   548.4    .045       0   563.4     .12       0
Bank Sta=548.4,563.4
XS Rating Curve= 0 ,0
Exp/Cntr=0.3,0.1

Type RM Length L Ch R = 1 ,19176   ,450.8,445,436.3
XS GIS Cut Line= 2
     2153131.451      221872.825     2152700.896        222919.7
#Sta/Elev= 30
       0 2569.36     9.8 2566.73    65.4 2545.88    94.9 2536.34   160.3 2521.41
   196.3 2511.54   235.6 2499.02   287.9 2485.76   333.7 2475.56   363.1  2470.5
   402.4 2467.26     530 2461.82   552.9 2461.65   566.1 2458.68   572.5 2457.36
   581.1  2458.8   592.2 2460.21     615 2459.01   641.2 2462.01   700.1 2464.73
   729.6 2467.13     880  2472.2   922.6 2475.47   935.7 2474.88   974.9 2476.42
   994.6 2473.46  1004.4 2476.63  1030.5 2495.36  1040.4 2500.43    1132 2532.76
#Mann= 3 ,-1 , 0
       0     .12       0   566.1    .045       0   581.1     .12       0
#XS Ineff= 2 , 0
          551.83 2463.67
Permanent Ineff=
       F       F
Bank Sta=566.1,581.1
XS Rating Curve= 0 ,0
Exp/Cntr=0.3,0.1

Type RM Length L Ch R = 1 ,18731   ,342.1,344.2,347.7
XS GIS Cut Line= 2
     2152681.798      221733.936     2152589.784      222853.728
#Sta/Elev= 30
       0 2561.79    65.5 2544.53   127.8 2531.96     154  2525.3   252.2 2496.92
   314.5  2484.6   330.8 2479.21   340.7 2478.33   353.8 2474.24     380 2470.32
   393.1 2469.72   402.9 2467.48   432.4 2468.04   448.8 2464.33   471.7 2463.04
   491.4 2456.22   524.1 2454.55   532.2 2452.88   540.5 2452.27   547.2    2453
   576.5 2458.17   635.5  2458.6   818.9 2466.68   871.3 2467.39   907.4 2469.64
   923.8 2472.94   933.6 2473.26  1015.5 2505.95  1041.7 2514.18  1123.6 2536.06
#Mann= 3 ,-1 , 0
       0     .12       0   532.2    .045       0   547.2     .12       0
#XS Ineff= 2 , 0
          498.57 2459.52
Permanent Ineff=
       F       F
Bank Sta=532.2,547.2
XS Rating Curve= 0 ,0
Exp/Cntr=0.3,0.1

Type RM Length L Ch R = 1 ,18386.8 ,344.4,351.1,354
XS GIS Cut Line= 3
     2152400.484      221709.036     2152315.083      222247.411
     2152186.914      222788.782
#Sta/Elev= 30
       0 2529.84    35.9 2530.15   107.7 2528.47   264.4 2507.82   326.4 2498.08
   372.1 2488.71   385.2 2485.55   430.9 2470.41   443.9 2464.78   450.4 2464.99
   460.2 2461.58   486.4 2458.12   502.7  2453.8   525.5 2453.34   537.6 2448.97
   548.4 2448.66   552.6 2448.93   597.5  2453.4   643.3 2453.05   662.9 2451.94
   695.6 2454.05   767.6 2456.35   797.1 2460.04     820 2465.09   829.8 2465.69
   849.4 2472.27     892 2484.42   990.2  2511.1  1022.9 2518.45  1101.4 2549.41
#Mann= 3 ,-1 , 0
       0     .12       0   537.6    .045       0   552.6     .12       0
Bank Sta=537.6,552.6
XS Rating Curve= 0 ,0
Exp/Cntr=0.3,0.1

Type RM Length L Ch R = 1 ,18035.7 ,261.8,269.5,272.4
XS GIS Cut Line= 3
     2152225.069      221686.968     2151969.369       222240.26
     2151781.109      222740.455
#Sta/Elev= 30
       0 2555.76    72.1 2533.62   134.4 2521.13     249 2494.77   281.8 2484.08
   304.8 2474.73   327.7 2463.42   363.8 2452.63   406.4 2448.06   455.5 2448.29
   498.1 2446.01     521 2447.54   573.5 2447.68  600.042445.652  603.982444.678
   616.1  2444.3  619.972444.681   632.5 2449.38  665.362449.841   714.4 2451.64
   740.7 2462.82   750.5  2464.7   766.9 2472.74   793.1 2482.81   835.8 2494.13
   871.8 2497.41   983.3 2499.83  1016.1 2496.34  1055.4 2507.76    1144 2520.45
#Mann= 5 ,-1 , 0
       0     .12       0  600.04     .08       0  603.98    .045       0
  619.97     .08       0  665.36     .12       0
#XS Ineff= 2 , 0
          424.35 2449.79
Permanent Ineff=
       F       F
Bank Sta=603.98,619.97
XS Rating Curve= 0 ,0
Exp/Cntr=0.3,0.1