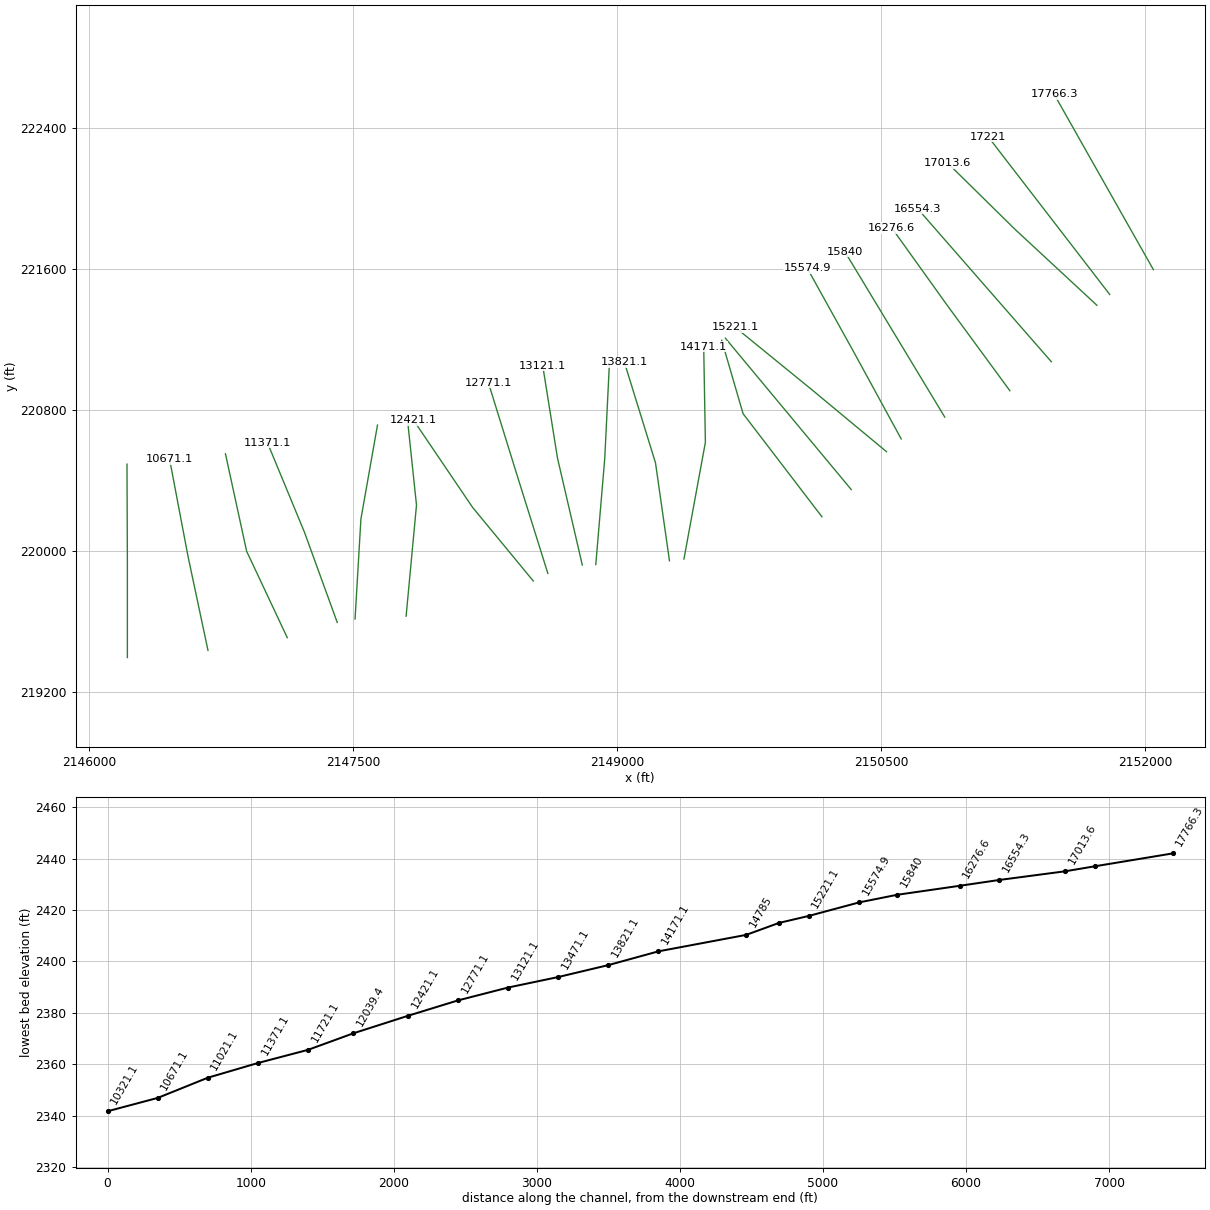
HEC-RAS study DEVILCK.prj: DEVILCK

--- DEVILCK.g01 (geometry) --- (continued)

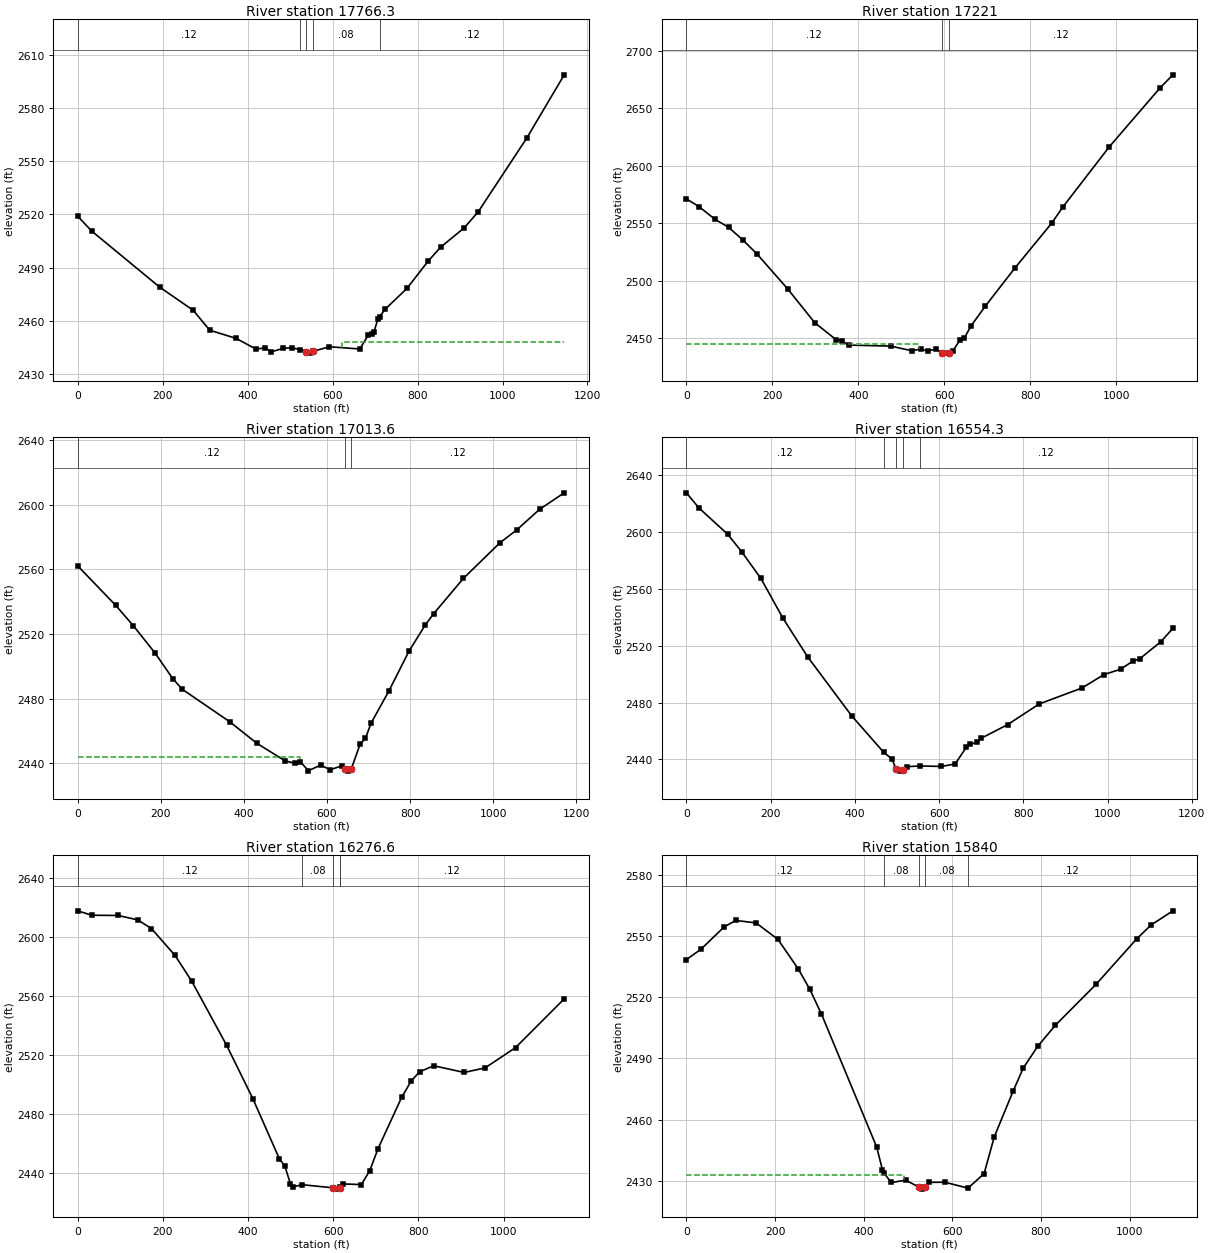
Type RM Length L Ch R = 1 ,17766.3 ,538.3,545.3,540.9
XS GIS Cut Line= 2
     2152046.382      221596.783     2151482.146      222593.311
#Sta/Elev= 30
       0 2518.98    32.7 2510.69     193 2479.09   271.6 2466.12   310.8 2454.87
     373 2450.26   418.8 2444.34   441.7 2444.85   454.8 2442.66   484.2  2444.7
   503.9 2444.99  523.582443.971  537.452442.883   546.4 2441.98     553 2442.92
   592.2 2445.56   664.2 2444.32   683.8 2452.08   693.6 2452.55   696.9 2453.66
   706.7 2461.19   710.8 2462.54   723.1 2466.55   775.4 2478.51   824.5 2493.61
     854 2501.54   909.6 2512.43   942.3 2521.35  1056.8 2562.88  1145.2 2598.57
#Mann= 5 ,-1 , 0
       0     .12       0  523.58     .08       0  537.45    .045       0
     553     .08       0   710.8     .12       0
#XS Ineff= 2 , 0
                           622.3         2448.33
Permanent Ineff=
       F       F
Bank Sta=537.45,553
XS Rating Curve= 0 ,0
Exp/Cntr=0.3,0.1

Type RM Length L Ch R = 1 ,17221   ,204.3,207.4,210.1
XS GIS Cut Line= 2
     2151798.118      221456.158     2151107.146      222351.992
#Sta/Elev= 30
       0 2571.26    29.5 2564.48    65.6 2553.73    98.4 2546.42   131.2 2535.47
     164 2523.36   236.1 2492.61   298.4 2463.46   347.6 2448.82   360.7 2447.76
   377.1    2444   475.5 2443.06   524.7    2439   544.4 2440.52   560.8 2438.75
   580.4 2440.53   593.6 2437.26   596.8 2436.97     610 2437.36   619.8 2439.09
   636.2 2448.33     646 2449.96   662.4 2460.93   695.2 2477.92   764.1 2511.16
   849.3 2550.04   875.6 2564.29   983.8 2616.78  1101.8 2668.06  1131.4 2679.32
#Mann= 3 ,-1 , 0
       0     .12       0   593.6    .045       0     610     .12       0
#XS Ineff= 2 , 0
          540.21  2445.2
Permanent Ineff=
       F       F
Bank Sta=593.6,610
XS Rating Curve= 0 ,0
Exp/Cntr=0.3,0.1

Type RM Length L Ch R = 1 ,17013.6 ,462.6,459.3,451.3
XS GIS Cut Line= 3
     2151725.056      221395.087     2151260.264      221825.718
      2150877.15      222202.399
#Sta/Elev= 30
       0 2562.19    91.4 2537.75   133.9 2525.12   186.2 2508.17   228.6 2492.39
   251.5 2485.77   365.8 2465.63   431.1 2452.27   499.7  2441.3   522.6 2440.01
   535.6 2440.92   555.2 2435.26   584.6 2438.77   607.5 2435.89   636.9 2438.41
   643.4  2436.6     650 2435.03  658.792436.612   679.5 2451.63   692.6 2455.42
   705.7 2464.56   748.3 2484.41   797.4 2509.41   836.7 2525.69   856.4 2532.49
   928.5 2554.54  1016.9  2576.7  1056.2 2584.39  1111.9 2597.32  1170.9 2607.49
#Mann= 3 ,-1 , 0
       0     .12       0   643.4    .045       0  658.79     .12       0
#XS Ineff= 2 , 0
          533.97 2443.48
Permanent Ineff=
       F       F
Bank Sta=643.4,658.79
XS Rating Curve= 0 ,0
Exp/Cntr=0.3,0.1

Type RM Length L Ch R = 1 ,16554.3 ,279,277.7,275
XS GIS Cut Line= 2
     2151466.521      221074.214     2150706.104      221944.005
#Sta/Elev= 30
       0 2627.69    29.5 2617.09    98.2 2598.44   130.9 2586.31   176.7 2567.45
   229.1 2539.46     288 2512.11   392.7 2470.52  468.662444.856   487.7 2440.38
   498.2 2432.94   507.3 2431.67   513.2 2432.74   523.7 2434.79  554.252435.318
   605.5 2434.97   638.2 2436.74   664.4 2448.33   674.2 2450.54   690.6 2452.05
   700.4 2454.89   762.6  2464.4   837.8 2478.99   939.3 2490.21   991.7  2499.7
    1031 2503.43  1060.4 2509.17  1076.8 2510.85  1125.9 2522.62  1155.3 2532.17
#Mann= 5 ,-1 , 0
       0     .12       0  468.66     .08       0   498.2    .045       0
   513.2     .08       0  554.25     .12       0
Bank Sta=498.2,513.2
XS Rating Curve= 0 ,0
Exp/Cntr=0.3,0.1

Type RM Length L Ch R = 1 ,16276.6 ,436.9,436.6,434.2
XS GIS Cut Line= 3
     2151230.852      220909.578      2150871.47      221398.992
     2150559.816      221833.905
#Sta/Elev= 30
       0 2617.61    32.6 2614.64    94.7 2614.45   140.4 2611.53     173 2605.64
   228.5 2587.42   267.7 2570.01   349.3  2526.8   411.3  2490.5   473.4 2449.92
   486.4 2444.84   499.5 2432.93     506 2430.98   526.62432.394   599.7  2430.3
   610.4  2429.4   614.7 2430.41  616.362430.915   623.5 2432.92   665.9 2432.48
   685.5 2441.81   705.1 2456.78   760.5 2491.46   783.4 2502.74   802.9 2508.74
   835.6 2512.84   907.3 2508.31   956.3 2511.36    1028 2525.13  1142.2 2558.08
#Mann= 5 ,-1 , 0
       0     .12       0   526.6     .08       0   599.7    .045       0
   614.7     .08       0  616.36     .12       0
Bank Sta=599.7,614.7
XS Rating Curve= 0 ,0
Exp/Cntr=0.3,0.1

Type RM Length L Ch R = 1 ,15840   ,266,265.2,264.2
XS GIS Cut Line= 2
     2150860.618      220759.978     2150292.909      221699.214
#Sta/Elev= 30
       0 2538.47    32.8 2543.53    85.2  2554.5   111.4 2557.65   157.2 2556.44
   206.4 2548.36   252.3 2533.88   278.5 2523.84   304.7 2511.71   429.2 2446.56
   442.3  2435.3  445.07 2434.01   461.9 2429.16   494.7 2430.27   524.2 2426.97
   530.7 2425.91  538.742426.969   547.1 2429.22   583.1 2429.29  635.322426.399
   671.6 2433.55   694.5 2451.55   737.1 2473.99     760 2485.32   792.8 2496.01
   832.1 2506.21   923.8 2526.26  1015.6 2548.57  1048.3 2555.44  1097.5 2562.37
#Mann= 5 ,-1 , 0
       0     .12       0  445.07     .08       0   524.2    .045       0
  538.74     .08       0  635.32     .12       0
#XS Ineff= 2 , 0
          491.66  2432.6
Permanent Ineff=
       F       F
Bank Sta=524.2,538.74
XS Rating Curve= 0 ,0
Exp/Cntr=0.3,0.1

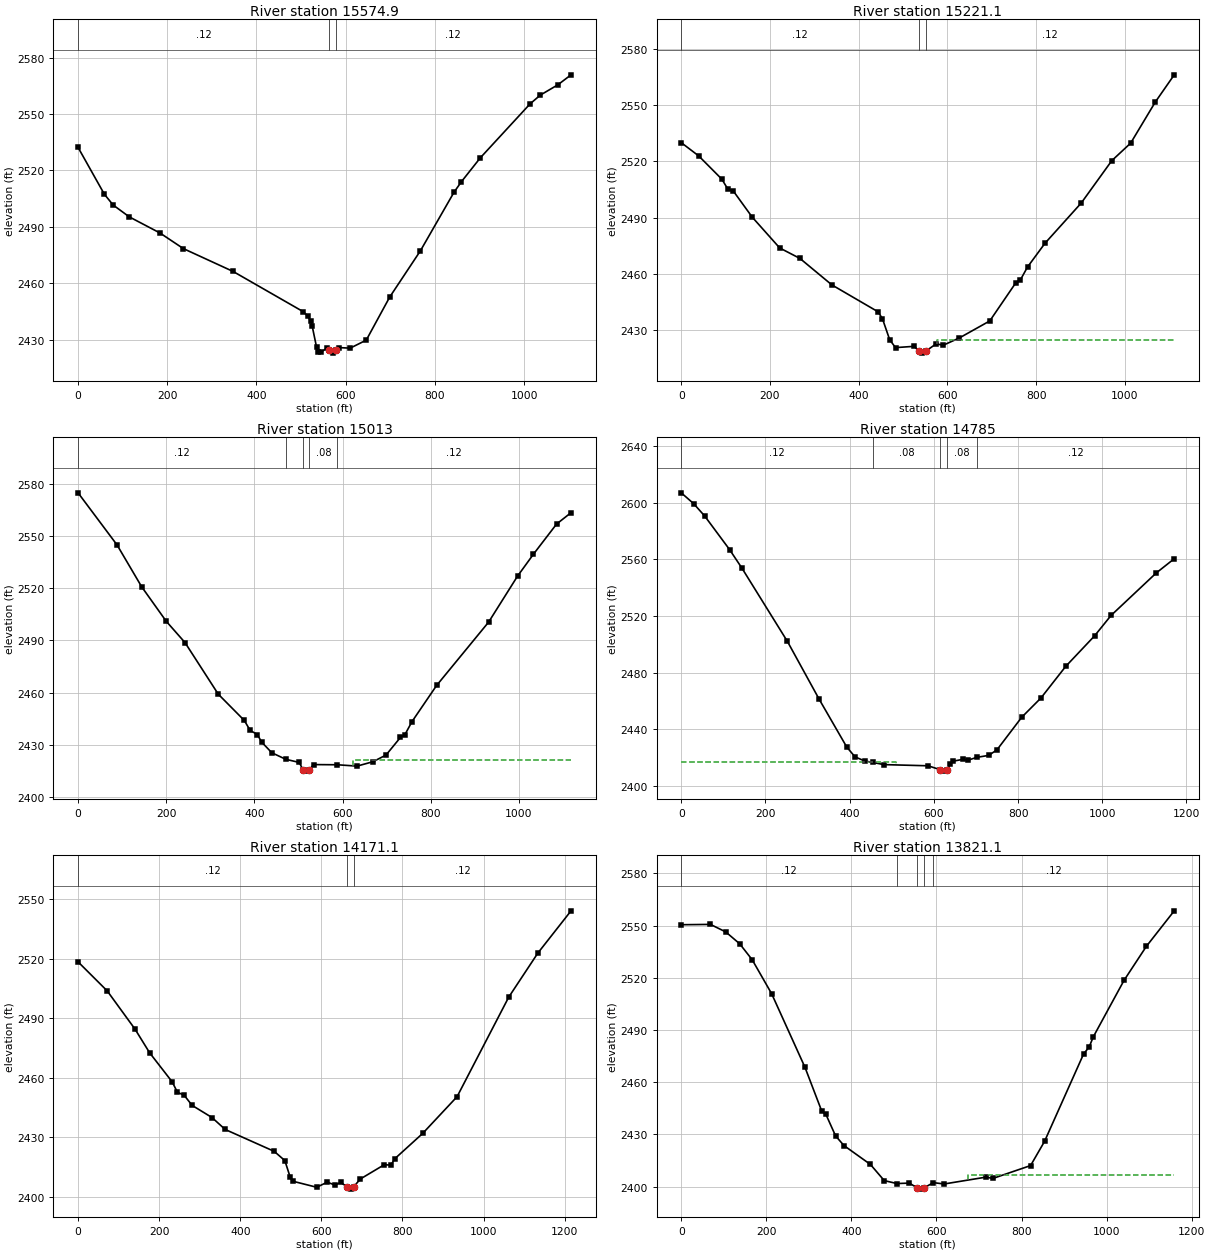
Type RM Length L Ch R = 1 ,15574.9 ,345.5,353.8,361.1
XS GIS Cut Line= 3
     2150613.302      220635.976     2150344.267      221128.253
      2150080.09      221604.155
#Sta/Elev= 30
       0 2532.25      59 2507.36    78.7 2501.64   114.8 2495.36   183.7 2486.78
   236.2 2478.48   347.8 2466.33   505.2 2444.93   515.1 2442.64   521.6  2439.9
   524.9 2437.35   534.8 2426.06     538 2423.72   544.6 2423.49   557.7 2425.59
  562.262424.664   570.8 2422.96   577.4 2424.62     584  2425.9   610.2 2425.62
   646.2 2429.87   698.7 2452.73   767.6 2477.33     843 2508.47   859.4    2514
     902 2526.75  1013.5  2555.4  1036.4 2560.04  1075.8 2565.52  1105.3 2570.82
#Mann= 3 ,-1 , 0
       0     .12       0  562.26    .045       0   577.4     .12       0
Bank Sta=562.26,577.4
XS Rating Curve= 0 ,0
Exp/Cntr=0.3,0.1

Type RM Length L Ch R = 1 ,15221.1 ,212,208.1,202.9
XS GIS Cut Line= 3
     2150529.748      220563.467     2150112.842      220909.318
     2149671.127      221268.938
#Sta/Elev= 30
       0 2530.03    39.2 2522.98    91.4 2510.56   104.4 2505.48   117.5 2504.16
   159.9 2490.29   221.9 2473.82   267.6 2468.22   339.4 2454.12   443.8 2439.72
   453.6 2435.99   469.9  2424.8     483 2420.62   525.4 2421.32   535.2 2418.82
   541.7 2417.68   551.5 2418.78   574.4 2422.61   590.8 2421.93   626.8 2425.77
   695.5 2434.87   754.5 2455.35   764.3 2456.69   780.6 2463.66   819.9 2476.32
   901.8 2497.85   970.5 2520.41  1013.1 2529.79  1068.7 2551.75  1111.3 2566.24
#Mann= 3 ,-1 , 0
       0     .12       0   535.2    .045       0   551.5     .12       0
#XS Ineff= 2 , 0
                          577.16         2424.49
Permanent Ineff=
       F       F
Bank Sta=535.2,551.5
XS Rating Curve= 0 ,0
Exp/Cntr=0.3,0.1

Type RM Length L Ch R = 1 ,15013   ,229.7,228,227.1
XS GIS Cut Line= 2
     2150329.368      220348.519      2149614.09      221207.894
#Sta/Elev= 30
       0  2574.8    88.5 2544.84   144.3 2520.82     200 2501.03   242.6 2488.78
     318 2459.16   377.1 2444.06   390.2 2438.39   406.6 2435.99   416.4 2431.65
   439.4 2425.53  471.122421.759   501.7 2419.96  509.882415.872   514.8 2414.97
   524.6  2415.9   534.5 2418.73   588.12418.624   632.8 2417.85   668.9 2420.38
   698.4 2424.19   731.2 2434.32     741 2435.78   757.4 2443.42   813.2 2464.17
   931.2 2500.57   996.8 2526.97  1032.8 2539.54  1085.3 2556.87  1118.1  2563.4
#Mann= 5 ,-1 , 0
       0     .12       0  471.12     .08       0  509.88    .045       0
   524.6     .08       0   588.1     .12       0
#XS Ineff= 2 , 0
                          623.03         2421.27
Permanent Ineff=
       F       F
Bank Sta=509.88,524.6
XS Rating Curve= 0 ,0
Exp/Cntr=0.3,0.1

Type RM Length L Ch R = 1 ,14785   ,627.5,613.9,599.9
XS GIS Cut Line= 3
     2150162.701      220194.005     2149714.784      220779.075
     2149593.257      221195.742
#Sta/Elev= 30
       0 2607.01    29.5 2599.33    55.7  2590.6   114.6 2566.96   144.1 2553.79
   252.2 2501.96   327.5 2461.16     393 2427.39   412.6 2420.44   435.6  2417.5
  454.382416.502   481.4 2414.95   586.2 2414.11   615.7 2411.29   625.5 2410.34
     632 2411.08   638.6 2415.48   645.2 2417.34   668.1 2418.62   681.2 2418.07
  701.382420.041   730.3 2421.47   749.9  2425.4   808.6 2448.39   854.3 2462.02
   913.1 2484.34   981.6  2505.9  1020.8 2520.35  1128.4 2550.44  1170.9 2560.43
#Mann= 5 ,-1 , 0
       0     .12       0  454.38     .08       0   615.7    .045       0
     632     .08       0  701.38     .12       0
#XS Ineff= 2 , 0
          510.53  2417.1
Permanent Ineff=
       F       F
Bank Sta=615.7,632
XS Rating Curve= 0 ,0
Exp/Cntr=0.3,0.1

Type RM Length L Ch R = 1 ,14171.1 ,342.4,350,355.7
XS GIS Cut Line= 3
     2149378.673      219954.174      2149500.48      220616.525
     2149491.008      221158.794
#Sta/Elev= 30
       0 2518.36    71.9 2503.73   140.6 2484.45   176.5 2472.58   232.1 2457.94
   245.2 2452.65   261.5 2451.26   281.2 2446.11   330.2    2440   362.9 2433.97
   483.8 2422.95     510  2418.3   523.1 2409.98   529.6 2407.92   588.5 2404.88
   614.6 2407.45   634.2 2405.94   647.3 2407.35   663.6  2405.1   673.5 2403.94
     680  2405.2   696.3 2409.06   755.1 2416.22   771.5 2416.04   781.3 2419.27
   849.9 2431.98   934.8  2450.5  1062.2 2500.62  1134.1 2522.82  1215.8 2544.05
#Mann= 3 ,-1 , 0
       0     .12       0   663.6    .045       0     680     .12       0
Bank Sta=663.6,680
XS Rating Curve= 0 ,0
Exp/Cntr=0.3,0.1

Type RM Length L Ch R = 1 ,13821.1 ,354.7,350,340.8
XS GIS Cut Line= 3
     2149296.453      219943.779     2149216.991      220500.358
     2149040.493      221070.314
#Sta/Elev= 30
       0 2550.47    68.6 2550.65   104.6 2546.33   137.3 2539.53   166.7 2530.36
   212.5 2510.82   290.9 2468.52   330.1 2443.49     340 2441.55   362.8 2429.17
   382.4 2423.64   444.6 2412.79   477.2  2403.5  507.162401.794   536.1 2402.07
   554.7 2399.34   562.2  2398.6   569.7 2399.25   592.8 2402.32     618 2401.56
   716.3 2405.49   732.7 2404.75   821.2 2412.13     854 2426.02   945.8 2476.23
   958.9 2480.26   968.7  2486.1  1040.9 2518.52  1093.3 2538.02  1158.9 2558.45
#Mann= 5 ,-1 , 0
       0     .12       0  507.16     .07       0   554.7    .045       0
   569.7     .07       0   592.8     .12       0
#XS Ineff= 2 , 0
                           675.1         2406.79
Permanent Ineff=
       F       F
Bank Sta=554.7,569.7
XS Rating Curve= 0 ,0
Exp/Cntr=0.3,0.1

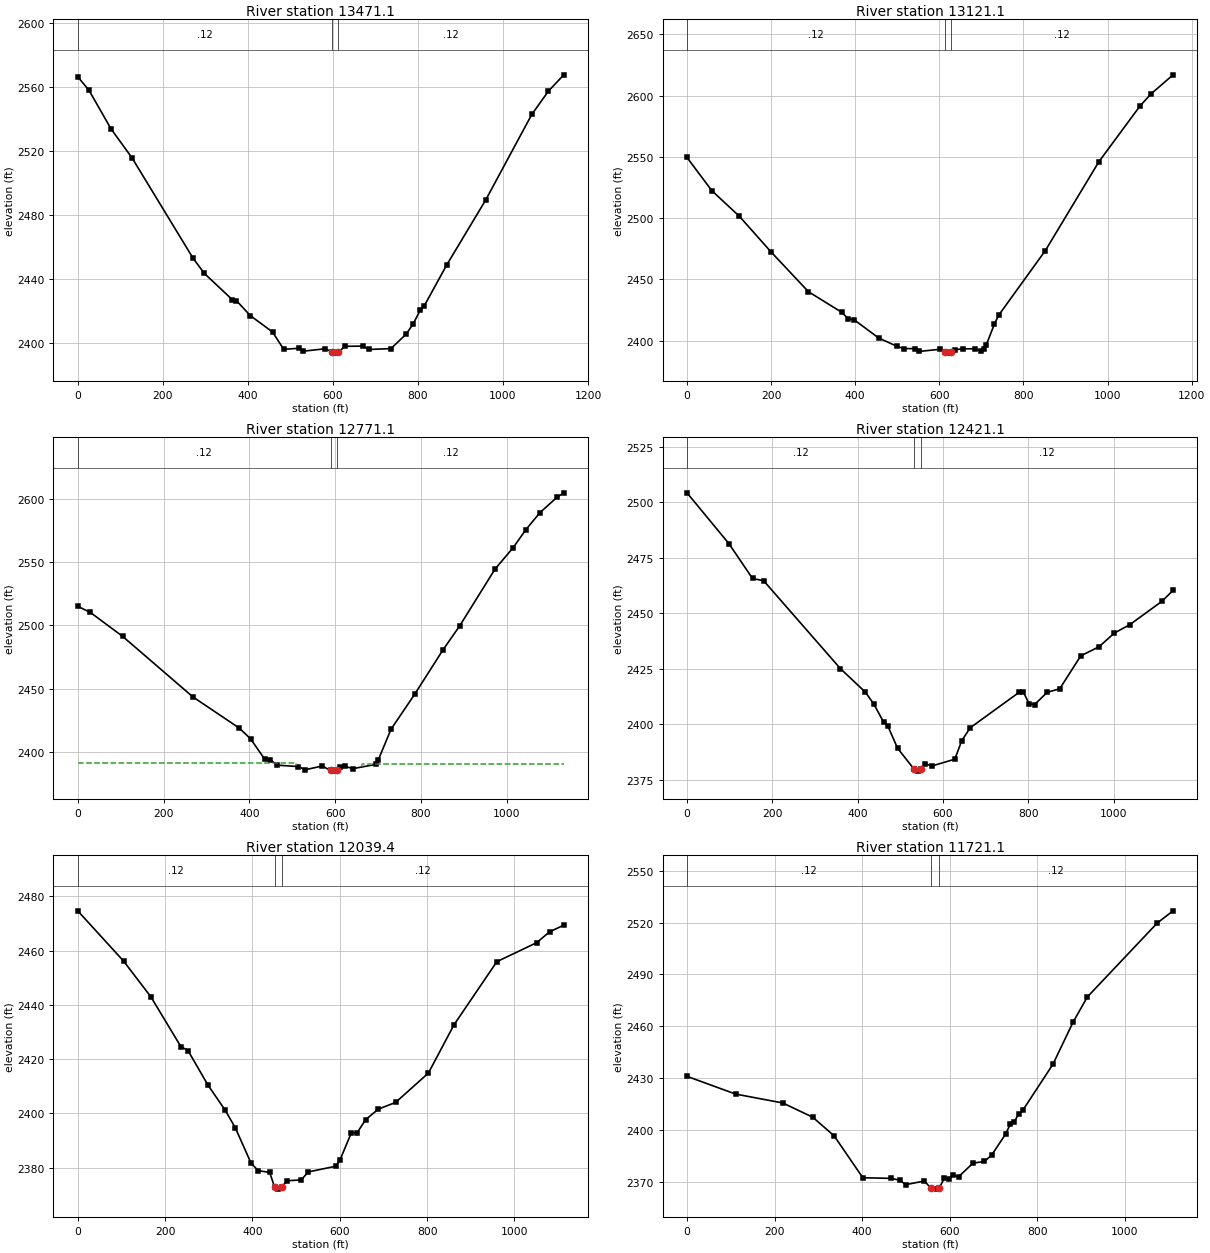
Type RM Length L Ch R = 1 ,13471.1 ,340.8,350,351.6
XS GIS Cut Line= 3
     2148877.751      219922.695     2148928.699       220525.91
     2148955.036      221062.898
#Sta/Elev= 30
       0 2566.38    26.2 2558.07    78.5  2533.8   127.6 2515.82   271.6 2453.02
   297.8  2443.7   363.2 2427.38     373 2426.79   405.8 2417.36   458.1 2407.16
   484.3 2396.37   520.3 2396.98   530.1 2395.18   582.5 2396.71   597.9 2394.67
   605.4 2393.97   612.9 2394.58   628.3 2398.23   670.9 2398.34     684 2396.26
   736.5 2396.77   772.6 2405.93     789  2412.3   805.3 2420.78   815.2 2423.63
   867.6 2448.97   959.4 2489.55  1067.6 2542.84  1106.9 2557.46    1143 2567.59
#Mann= 3 ,-1 , 0
       0     .12       0   597.9    .045       0   612.9     .12       0
Bank Sta=597.9,612.9
XS Rating Curve= 0 ,0
Exp/Cntr=0.3,0.1

Type RM Length L Ch R = 1 ,13121.1 ,348.8,350,350.5
XS GIS Cut Line= 3
     2148801.121      219919.867     2148660.122      220527.061
     2148576.016      221052.725
#Sta/Elev= 30
       0  2549.5      59 2522.44   124.7 2501.45   200.1 2472.34   288.7 2440.01
   367.4 2423.29   383.8 2417.85     397 2417.19     456 2402.17   498.7 2395.55
   515.1 2393.55   541.3 2393.62   551.2 2391.23   600.4 2392.99   613.5 2390.59
   620.1 2389.89  628.012390.523   636.4 2392.64     656 2393.41   685.4 2393.43
   698.5  2391.7     705 2392.94   711.5 2396.58   731.1  2413.8   740.9 2420.75
     852 2473.55   979.3 2546.02  1077.3 2591.59  1103.4 2601.39  1155.7 2616.89
#Mann= 3 ,-1 , 0
       0     .12       0   613.5    .045       0  628.01     .12       0
Bank Sta=613.5,628.01
XS Rating Curve= 0 ,0
Exp/Cntr=0.3,0.1

Type RM Length L Ch R = 1 ,12771.1 ,338.9,350,357.1
XS GIS Cut Line= 3
      2148605.32      219872.485     2148426.941      220441.102
     2148267.719       220954.15
#Sta/Elev= 30
       0 2515.14    29.5 2510.27   104.8 2491.35   268.5 2443.54   376.6  2418.9
   402.8 2410.46   435.5 2394.52   448.6 2393.99     465 2389.62   514.1 2388.52
   530.4    2386   569.7 2388.91   589.4  2385.5   599.2  2384.9  604.412385.583
   612.3 2388.19   622.1 2388.71   641.8 2386.88   694.2 2390.18   700.8 2393.88
   730.2 2417.94   785.9  2445.9   851.4 2480.68   890.7 2499.84   972.6 2544.46
  1015.2 2561.56  1044.7 2575.72  1077.4 2589.12  1116.8 2601.15  1133.1 2604.79
#Mann= 3 ,-1 , 0
       0     .12       0   589.4    .045       0  604.41     .12       0
#XS Ineff= 2 , 0
          509.86 2391.32  662.65         2390.69
Permanent Ineff=
       F       F
Bank Sta=589.4,604.41
XS Rating Curve= 0 ,0
Exp/Cntr=0.3,0.1

Type RM Length L Ch R = 1 ,12421.1 ,399.2,381.7,364.9
XS GIS Cut Line= 3
     2148522.606      219829.166      2148177.33      220247.697
     2147842.376      220741.835
#Sta/Elev= 30
       0 2504.32    98.1 2481.47   153.6 2465.74   179.8 2464.69   359.5 2425.14
   418.4 2414.46     438 2409.12   460.9 2401.02   470.7 2399.31   493.5 2389.28
   532.8 2379.69   542.6 2378.92   549.1 2379.74     559 2382.15   575.4 2381.31
   627.8  2384.3   644.2 2392.68   663.9 2398.45   778.7 2414.45   788.6 2414.55
   801.7 2409.35   814.8  2408.9   844.3 2414.43   873.8 2416.02     923 2430.86
   965.7 2434.93  1001.8 2441.13  1037.9  2444.9  1113.3 2455.44  1139.5 2460.38
#Mann= 3 ,-1 , 0
       0     .12       0   532.8    .045       0   549.1     .12       0
Bank Sta=532.8,549.1
XS Rating Curve= 0 ,0
Exp/Cntr=0.3,0.1

Type RM Length L Ch R = 1 ,12039.4 ,317.3,318.3,317.1
XS GIS Cut Line= 3
     2147799.854      219629.769     2147858.882      220259.978
     2147808.534      220737.408
#Sta/Elev= 30
       0 2474.63     105 2456.12   167.3    2443   236.1 2424.63   252.5 2423.15
   298.4 2410.39   337.8 2401.16   360.8 2394.72   396.8 2381.72   413.2 2378.93
   439.5 2378.27  450.772372.907   459.2 2372.12  467.522372.894   478.8  2375.2
   511.6 2375.51     528 2378.46   590.3 2380.53   600.2 2382.74   626.4 2392.84
   639.5  2392.8   659.1 2397.69   688.5 2401.61   727.7 2404.04   802.8 2414.84
   861.6 2432.66   959.6  2455.9    1051 2462.91  1080.4  2466.9    1113 2469.36
#Mann= 3 ,-1 , 0
       0     .12       0  450.77    .045       0  467.52     .12       0
Bank Sta=450.77,467.52
XS Rating Curve= 0 ,0
Exp/Cntr=0.3,0.1

Type RM Length L Ch R = 1 ,11721.1 ,340.6,350,362.7
XS GIS Cut Line= 3
      2147509.79      219613.492     2147542.991      220180.676
       2147637.2      220714.517
#Sta/Elev= 30
       0 2430.97     111  2420.7   218.8 2415.55   287.3 2407.29   336.3 2396.44
   401.6 2372.26   466.9  2371.9   486.5 2370.75   499.6 2368.26     542 2370.36
  557.572366.156   571.4 2365.67   575.7 2366.12   587.8 2372.03   597.5 2371.74
   607.3 2373.65   620.4 2372.84   653.1  2380.7   679.2  2381.7   695.5 2385.25
   728.2 2397.74     738 2403.13   747.8 2404.79   757.6 2409.18   767.4 2411.49
   835.9 2438.01   881.6 2462.24   914.3 2476.91  1074.3 2519.78  1110.2 2526.78
#Mann= 3 ,-1 , 0
       0     .12       0  557.57    .045       0   575.7     .12       0
Bank Sta=557.57,575.7
XS Rating Curve= 0 ,0
Exp/Cntr=0.3,0.1

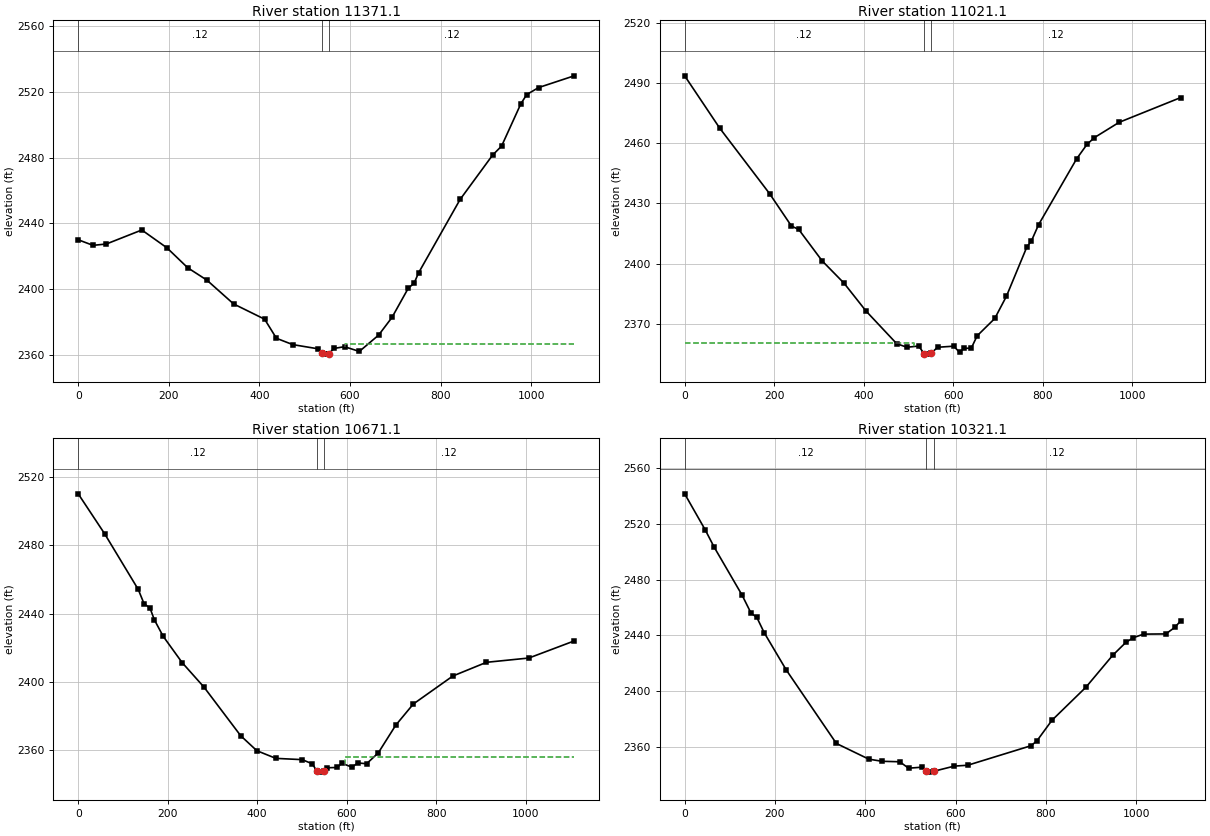
Type RM Length L Ch R = 1 ,11371.1 ,347.7,350,345.5
XS GIS Cut Line= 3
     2147408.555      219593.889     2147222.166      220106.455
     2147012.004      220614.047
#Sta/Elev= 30
       0 2430.05    32.7 2426.65      62 2427.47   140.4 2435.99     196 2425.12
   241.7 2413.04   284.1 2405.51   342.9 2391.08   411.5 2381.78   437.6 2370.18
   473.6 2366.34   529.1 2363.81   537.9 2360.96   545.4 2360.56   552.9 2360.86
     565 2364.04   587.9 2365.07   620.6  2362.2   663.1  2372.1   692.6 2382.83
   728.5 2400.56   741.6 2403.74   751.4 2409.96     843 2454.53   914.9 2481.54
   934.6 2486.96   977.1 2512.65   990.1 2518.28  1016.3 2522.52  1094.8 2529.66
#Mann= 3 ,-1 , 0
       0     .12       0   537.9    .045       0   552.9     .12       0
#XS Ineff= 2 , 0
                          588.88         2366.95
Permanent Ineff=
       F       F
Bank Sta=537.9,552.9
XS Rating Curve= 0 ,0
Exp/Cntr=0.3,0.1

Type RM Length L Ch R = 1 ,11021.1 ,354.8,350,348.8
XS GIS Cut Line= 3
     2147124.546       219507.55     2146893.554       219998.41
     2146773.249      220551.339
#Sta/Elev= 30
       0 2493.65    78.4 2467.53   189.6 2434.93   238.6 2418.74   254.9 2417.03
   307.2 2401.37   356.2 2390.22   405.2 2376.37   473.9 2360.04   496.7 2358.28
   522.9 2358.88     535 2355.16   545.8 2354.85     550 2355.17   565.4 2358.28
   601.4 2358.81   614.4 2355.71   624.3 2357.72   640.6 2357.85   653.7 2363.99
     693 2372.62   719.1 2383.71   764.9 2408.38   774.7  2411.2   791.1 2419.46
   876.1 2452.29     899 2459.41   915.4 2462.79     971 2470.46  1108.4 2482.79
#Mann= 3 ,-1 , 0
       0     .12       0     535    .045       0     550     .12       0
#XS Ineff= 2 , 0
          512.22 2360.56
Permanent Ineff=
       F       F
Bank Sta=535,550
XS Rating Curve= 0 ,0
Exp/Cntr=0.3,0.1

Type RM Length L Ch R = 1 ,10671.1 ,354.6,350,345.8
XS GIS Cut Line= 3
     2146673.987      219435.596     2146561.019      219966.904
     2146455.493      220522.229
#Sta/Elev= 30
       0 2510.27    58.9  2486.9   134.2 2454.16   147.2 2445.77   160.3 2443.34
   170.2 2436.36   189.8 2426.73   232.3 2411.25   281.4 2396.78   363.2 2368.35
   399.2 2359.58   441.8 2355.08   500.6 2354.33   523.6 2351.83  532.882347.685
   543.2 2347.01     549 2347.69   556.2 2349.57   579.1 2349.74   588.9 2352.26
   611.8 2349.91   624.9 2352.42   644.5 2351.92   670.6 2358.29   709.8 2374.59
     749 2386.98   837.2 2403.38   912.4 2411.43  1007.2 2413.95  1108.4 2423.96
#Mann= 3 ,-1 , 0
       0     .12       0  532.88    .045       0     549     .12       0
#XS Ineff= 2 , 0
                           596.9         2355.81
Permanent Ineff=
       F       F
Bank Sta=532.88,549
XS Rating Curve= 0 ,0
Exp/Cntr=0.3,0.1

Type RM Length L Ch R = 1 ,10321.1 ,289,291.5,293.4
XS GIS Cut Line= 3
     2146215.951      219394.757     2146215.951      219939.438
     2146213.748      220492.908
#Sta/Elev= 30
       0  2541.6    45.7  2515.6    65.2 2503.39   127.2 2468.82   146.8 2456.05
   159.8 2452.89   176.1 2441.92     225 2415.14   335.9 2362.42   407.7 2351.16
     437 2349.62   476.2 2349.28   495.8 2344.66   525.1 2345.38   534.9 2342.43
   541.4 2341.84   551.2 2342.42   597.1 2346.17   626.6 2346.77   767.4 2360.84
   780.5 2364.52   813.2 2379.02   888.6 2402.82   947.5 2425.59     977 2434.97
   993.4 2438.34  1016.3  2440.9  1065.4 2441.04  1085.1 2445.68  1098.2 2450.35
#Mann= 3 ,-1 , 0
       0     .12       0   534.9    .045       0   551.2     .12       0
Bank Sta=534.9,551.2
XS Rating Curve= 0 ,0
Exp/Cntr=0.3,0.1