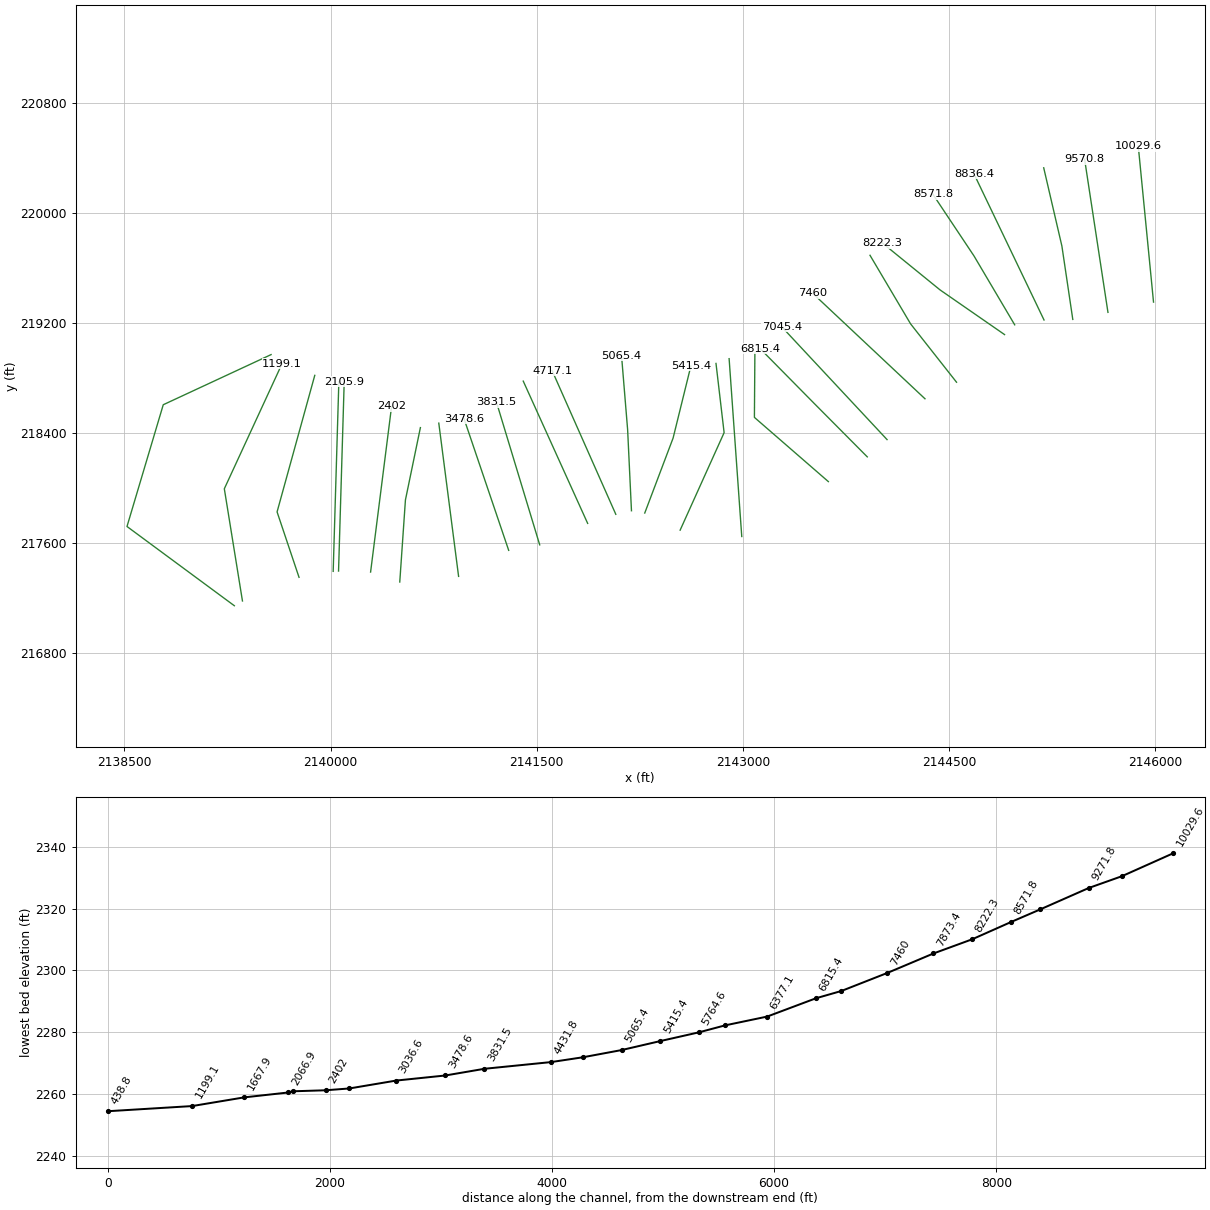
HEC-RAS study DEVILCK.prj: DEVILCK

--- DEVILCK.g01 (geometry) --- (continued)

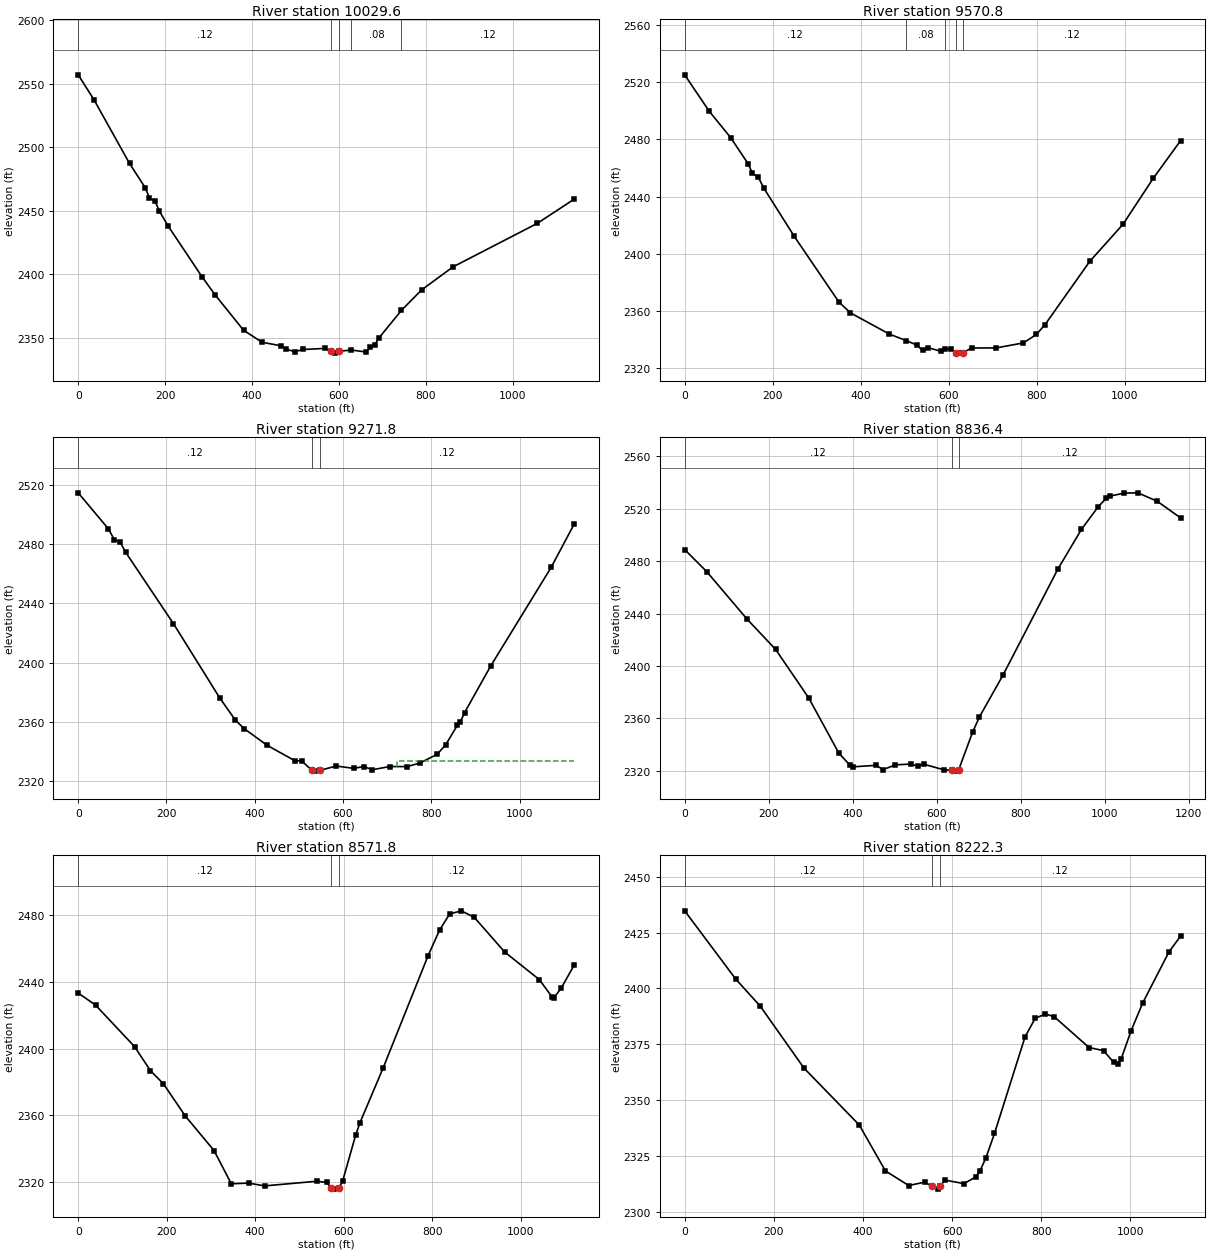
Type RM Length L Ch R = 1 ,10029.6 ,448.3,458.8,453.1
XS GIS Cut Line= 2
      2145989.09      219350.255     2145877.979      220485.672
#Sta/Elev= 30
       0 2556.88    36.1 2537.38     118 2487.16   154.1 2468.06   163.9  2460.1
     177  2457.3   186.9 2449.48   206.5 2438.07   285.2 2397.76   314.7 2383.79
   380.3  2355.9   422.9 2346.42   465.5 2343.71   478.6 2340.87   498.3 2339.07
     518 2340.75   567.1 2341.57   581.6 2339.38   590.1 2337.87   599.9 2339.38
  628.342340.293   662.2 2338.78     672 2342.59   681.9 2344.29   691.7 2349.79
  743.492371.528   790.1 2387.66   862.2 2405.75  1055.6  2439.9  1140.8 2459.02
#Mann= 5 ,-1 , 0
       0     .12       0   581.6    .045       0   599.9     .12       0
  628.34     .08       0  743.49     .12       0
Bank Sta=581.6,599.9
XS Rating Curve= 0 ,0
Exp/Cntr=0.3,0.1

Type RM Length L Ch R = 1 ,9570.8  ,299.6,299,300.4
XS GIS Cut Line= 2
     2145657.493      219275.603     2145487.354      220390.186
#Sta/Elev= 30
       0 2525.07    55.7 2499.65   104.9 2481.04   144.2 2462.91     154 2456.21
   167.2 2453.55   180.3 2445.68   249.1 2412.15   350.7 2366.19   376.9 2358.63
   465.4 2343.79  503.082339.327   527.7 2336.17   540.8 2332.46   553.9 2334.22
   583.4 2331.77  592.082333.271   606.4 2333.28   616.2 2330.76   629.3  2330.5
   633.42330.898   652.2 2334.09     708 2334.14   770.2 2337.64   799.7  2343.6
   819.4 2350.48     921 2394.68   996.4 2420.53  1065.2 2452.69  1127.5 2479.08
#Mann= 5 ,-1 , 0
       0     .12       0  503.08     .08       0  592.08     .12       0
   616.2    .045       0   633.4     .12       0
Bank Sta=616.2,633.4
XS Rating Curve= 0 ,0
Exp/Cntr=0.3,0.1

Type RM Length L Ch R = 1 ,9271.8  ,427.4,435.4,439.9
XS GIS Cut Line= 3
     2145401.552      219224.378     2145322.268      219757.747
     2145189.912      220326.925
#Sta/Elev= 30
       0 2514.65    68.6 2490.26    81.7 2483.02    94.8 2481.43   107.8 2474.35
   215.7 2426.33   320.3 2376.28   356.2 2361.07   375.8 2355.42   428.1  2344.1
   490.2 2333.82   506.6 2333.49   529.4 2327.23     536 2326.68   546.7 2327.16
   584.9 2330.11   624.1 2328.55     647 2329.78   666.6 2327.62   705.7 2329.78
   744.9 2329.73   774.3 2332.15   813.5  2338.1     833 2344.65   859.2 2357.77
   865.7 2359.89   875.5 2366.27   934.2 2397.52  1071.4 2464.25  1123.6 2493.52
#Mann= 3 ,-1 , 0
       0     .12       0   529.4    .045       0   546.7     .12       0
#XS Ineff= 2 , 0
                          721.86         2333.23
Permanent Ineff=
       F       F
Bank Sta=529.4,546.7
XS Rating Curve= 0 ,0
Exp/Cntr=0.3,0.1

Type RM Length L Ch R = 1 ,8836.4  ,262.8,264.6,267.3
XS GIS Cut Line= 2
     2145192.215      219220.047     2144681.798      220284.283
#Sta/Elev= 30
       0 2488.85    52.5 2472.03   147.5 2436.13   216.4 2412.68   295.1 2375.69
   367.2 2333.38   393.4 2324.29     400 2323.04   455.7 2324.21   472.1 2320.91
   501.6 2324.58   537.7 2325.17   554.1 2323.69   570.5 2324.92   616.4 2320.83
     636  2320.5   645.9 2319.78   651.9  2320.6   685.2 2349.52   701.6 2361.21
   757.4 2392.96   888.5 2474.18   944.2 2504.24   983.6 2521.32  1003.3 2528.03
  1013.1 2529.76  1045.9 2531.93  1078.7 2532.18  1124.6 2525.75  1180.3    2513
#Mann= 3 ,-1 , 0
       0     .12       0     636    .045       0   651.9     .12       0
Bank Sta=636,651.9
XS Rating Curve= 0 ,0
Exp/Cntr=0.3,0.1

Type RM Length L Ch R = 1 ,8571.8  ,339.7,349.5,356.5
XS GIS Cut Line= 3
     2144978.786      219184.945     2144683.035      219685.117
       2144383.6      220134.266
#Sta/Elev= 30
       0 2433.25    39.2 2426.02   127.3 2401.14   163.2 2386.73   192.6 2378.84
   241.6 2359.66   306.9 2338.83     346 2318.87   385.2 2319.29   421.1  2317.6
   538.6 2320.38   561.5  2319.7   572.12316.137   577.8 2315.67   588.6 2316.13
   597.4 2320.27   626.9 2347.92   636.7 2355.46     689 2388.22   790.4  2455.4
   816.6 2470.96   839.5 2480.66   865.7 2482.56   895.1 2478.66   963.8 2457.88
  1042.4 2441.26  1071.8 2430.64  1075.1 2430.46  1091.4 2436.08  1120.9 2450.02
#Mann= 3 ,-1 , 0
       0     .12       0   572.1    .045       0   588.6     .12       0
Bank Sta=572.1,588.6
XS Rating Curve= 0 ,0
Exp/Cntr=0.3,0.1

Type RM Length L Ch R = 1 ,8222.3  ,354.7,348.8,339.7
XS GIS Cut Line= 3
     2144904.987       219113.91     2144435.367      219439.004
     2144015.055      219780.507
#Sta/Elev= 30
       0 2434.77   114.2 2404.28   169.7 2392.02   267.6 2364.33   391.7 2338.82
   450.4 2318.25   502.6  2311.7   538.5 2313.22   554.8 2311.38   567.9 2310.09
  572.922311.365   584.2 2314.13   626.6 2312.56   652.7 2315.49   662.5  2318.3
   675.6 2323.95   695.1 2335.02   763.6 2378.27   786.5 2386.64   809.3 2388.53
   828.9 2387.37   907.2 2373.53   939.8 2372.14   962.6 2366.84   972.4  2366.3
     979 2368.27  1001.8 2381.15  1027.9  2393.6  1086.6 2416.38  1112.7 2423.46
#Mann= 3 ,-1 , 0
       0     .12       0   554.8    .045       0  572.92     .12       0
Bank Sta=554.8,572.92
XS Rating Curve= 0 ,0
Exp/Cntr=0.3,0.1

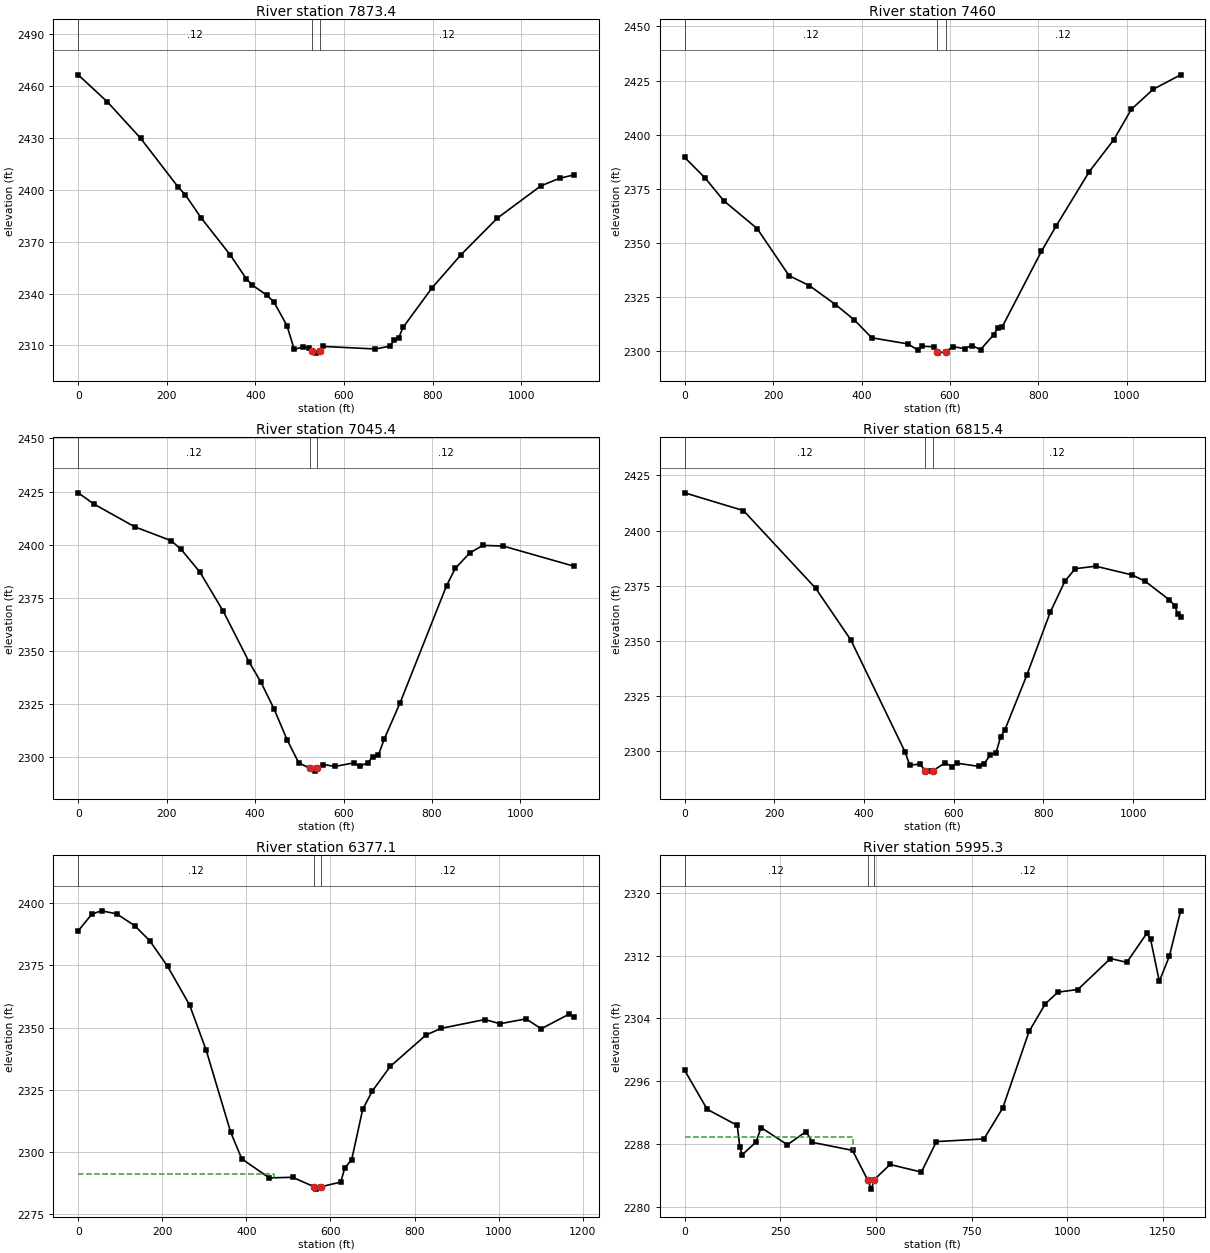
Type RM Length L Ch R = 1 ,7873.4  ,397,413.4,420.7
XS GIS Cut Line= 3
     2144555.486      218767.588      2144221.19      219191.772
     2143925.846      219690.528
#Sta/Elev= 30
       0 2466.53    65.5 2450.97   140.8 2429.85   225.8 2401.53   242.2 2396.96
   278.2 2383.52   343.7 2362.17   379.7 2348.45   392.8  2344.9   425.5 2339.11
   441.9 2335.09   471.3 2321.44   487.7 2307.61   507.4 2309.15   520.4 2308.27
     527 2306.63   536.8  2305.5  545.522306.654   553.2 2309.36   671.1 2307.91
   703.8 2309.54   713.6 2313.01   723.5 2314.28   733.3 2320.35   798.8 2343.25
   864.3 2362.45   946.2 2383.59  1044.4 2402.25    1087  2406.7  1119.7 2408.63
#Mann= 3 ,-1 , 0
       0     .12       0     527    .045       0  545.52     .12       0
Bank Sta=527,545.52
XS Rating Curve= 0 ,0
Exp/Cntr=0.3,0.1

Type RM Length L Ch R = 1 ,7460    ,415.3,414.6,411.2
XS GIS Cut Line= 2
     2144325.896       218647.13     2143508.187      219414.492
#Sta/Elev= 30
       0 2389.55    45.9 2380.11    88.5 2369.53   163.9  2356.7   236.1 2334.97
     282 2330.39     341 2321.65   383.6 2314.55     423  2306.3     505 2303.48
   527.9 2300.54   537.7  2302.4     564 2302.18  571.632299.901   573.8 2299.23
   590.2 2299.95   606.6 2302.19   632.8 2301.35   649.2 2302.75   668.9 2300.85
   698.4 2307.63   708.2 2310.89   718.1  2311.4   806.6 2346.18   839.4 2357.73
   914.8 2382.96   970.6  2397.8  1009.9 2411.73  1059.1 2420.95  1121.4 2427.66
#Mann= 3 ,-1 , 0
       0     .12       0  571.63    .045       0   590.2     .12       0
Bank Sta=571.63,590.2
XS Rating Curve= 0 ,0
Exp/Cntr=0.3,0.1

Type RM Length L Ch R = 1 ,7045.4  ,229.2,230,230.6
XS GIS Cut Line= 2
     2144049.854      218350.255     2143284.229        219169.7
#Sta/Elev= 30
       0 2424.41    36.1 2419.05   127.9  2408.4   209.9 2401.91   232.8 2397.78
   275.4 2387.02   327.9 2368.67   386.9 2344.61   413.2 2335.28   442.7 2322.73
   472.2 2308.24   498.4 2297.37  523.142294.761   534.5 2293.38     541 2294.76
   554.2  2296.5   580.4 2295.59     623 2297.24   636.2  2295.6   655.8 2297.42
   665.7 2300.21   678.8  2300.9   691.9 2308.42     728 2325.62   832.9 2380.66
   852.6 2388.81   885.4 2396.09   914.9 2399.67   960.8 2399.36  1121.5 2389.84
#Mann= 3 ,-1 , 0
       0     .12       0  523.14    .045       0     541     .12       0
Bank Sta=523.14,541
XS Rating Curve= 0 ,0
Exp/Cntr=0.3,0.1

Type RM Length L Ch R = 1 ,6815.4  ,436.4,438.3,438.8
XS GIS Cut Line= 3
     2143905.852      218224.649     2143522.262      218610.661
     2143127.637       219010.24
#Sta/Elev= 30
       0  2417.1   131.1 2409.04   291.8 2373.92   370.4 2350.46   491.7 2299.58
   501.6 2293.74   524.5 2294.16   536.7 2291.24   544.2 2291.01     554  2291.2
   580.1 2294.72   596.4  2293.1   606.2 2294.62   655.2 2293.19   668.3 2294.46
   681.3 2298.39   694.4 2299.39   704.2  2306.4     714 2309.74     763 2334.55
   815.2 2363.05   847.8 2377.06   870.7 2382.72   916.4 2383.86     998 2379.88
  1027.4 2376.94  1079.7 2368.75  1092.7 2366.04  1099.3 2362.02  1105.8 2360.92
#Mann= 3 ,-1 , 0
       0     .12       0   536.7    .045       0     554     .12       0
Bank Sta=536.7,554
XS Rating Curve= 0 ,0
Exp/Cntr=0.3,0.1

Type RM Length L Ch R = 1 ,6377.1  ,399.2,381.8,362.9
XS GIS Cut Line= 3
     2143622.771        218044.7     2143084.576      218511.714
     2143088.048      218978.728
#Sta/Elev= 30
       0 2388.87    32.7 2395.62    55.6 2396.89    91.5 2395.67     134 2390.97
     170 2384.92   212.5 2374.61   264.8  2359.1     304  2341.1   362.8 2307.89
     389 2297.28   454.3 2289.61   509.9 2289.85   561.22286.049   565.5  2285.1
   577.2 2286.05   624.3 2287.92   634.1 2293.62   650.5 2296.93   676.6 2317.14
   699.5 2324.48     742 2334.36   826.9 2346.96   862.8 2349.66   967.3 2353.22
  1003.2 2351.54  1065.3 2353.49  1101.2 2349.52  1166.5 2355.29  1179.6 2354.44
#Mann= 3 ,-1 , 0
       0     .12       0   561.2    .045       0   577.2     .12       0
#XS Ineff= 2 , 0
          466.69 2290.99
Permanent Ineff=
       F       F
Bank Sta=561.2,577.2
XS Rating Curve= 0 ,0
Exp/Cntr=0.3,0.1

Type RM Length L Ch R = 1 ,5995.3  ,240.8,230.6,219
XS GIS Cut Line= 2
     2142992.562      217645.394     2142900.548      218938.797
#Sta/Elev= 30
       0 2297.37    58.9  2292.4   137.5 2290.36   144.1 2287.59   150.6 2286.61
   186.6 2288.24   199.7 2290.08   268.5 2287.89   317.6 2289.57     334 2288.19
   438.8 2287.17   478.1 2283.44   487.9 2282.23  495.522283.438     537 2285.37
   618.9  2284.4   658.2 2288.29   782.6 2288.63   831.7 2292.58   900.5 2302.34
     943 2305.86   975.8 2307.34  1028.2 2307.68  1113.3 2311.63  1155.9 2311.14
  1208.3 2314.84  1218.1  2314.1    1241 2308.73  1267.2 2311.92  1296.7 2317.71
#Mann= 3 ,-1 , 0
       0     .12       0   478.1    .045       0  495.52     .12       0
#XS Ineff= 2 , 0
          439.22 2288.92
Permanent Ineff=
       F       F
Bank Sta=478.1,495.52
XS Rating Curve= 0 ,0
Exp/Cntr=0.3,0.1

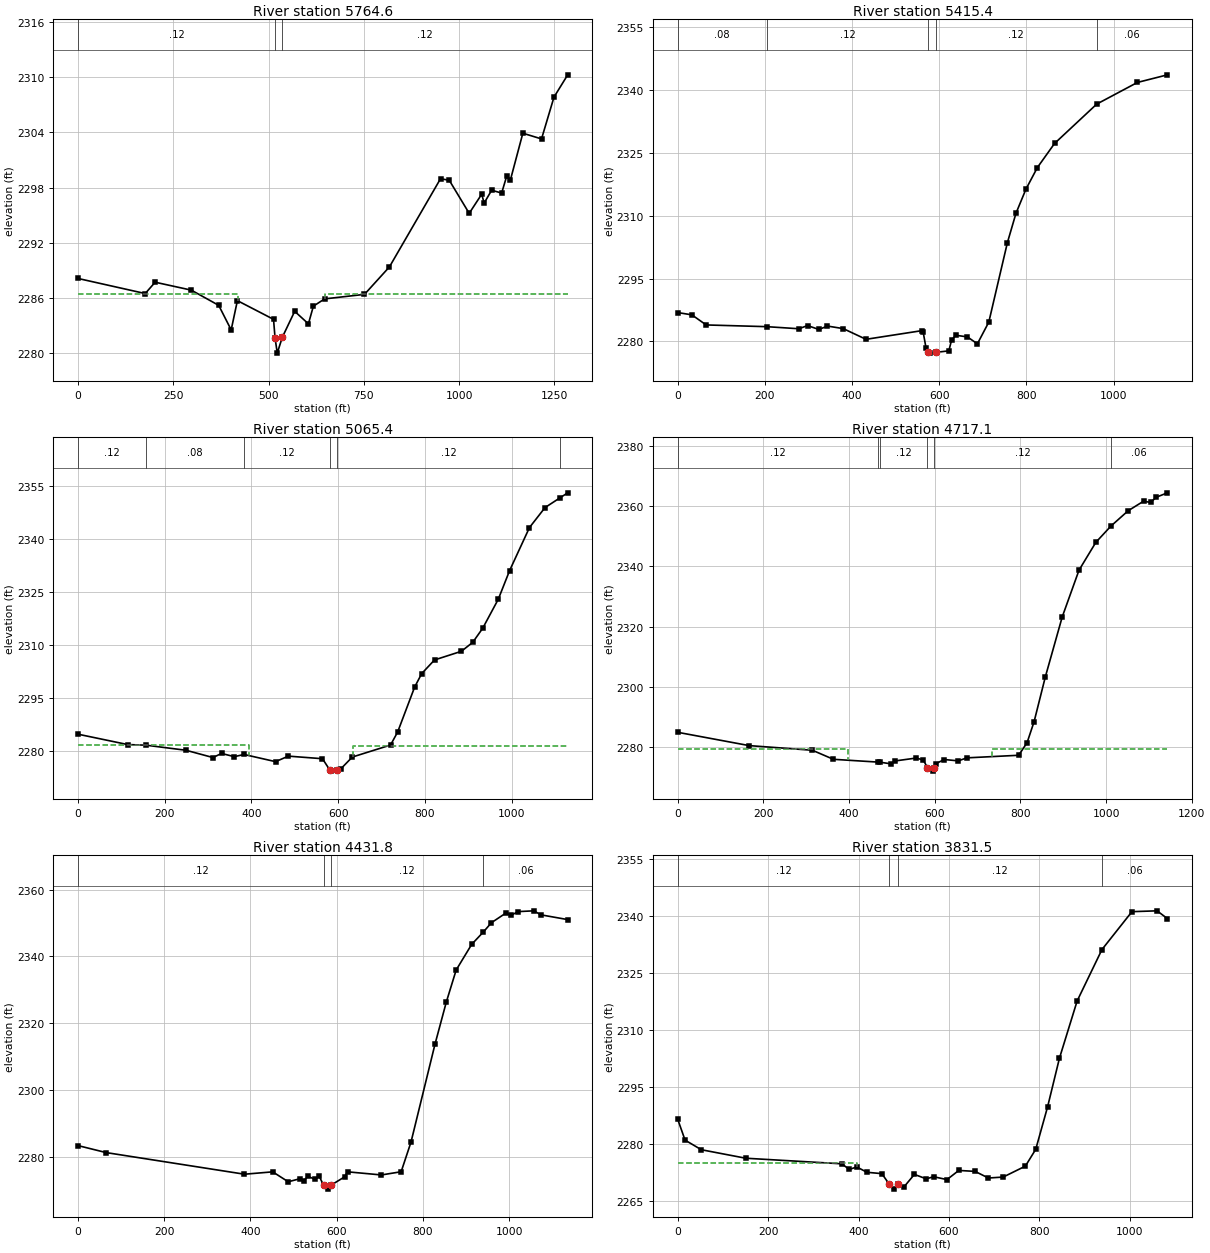
Type RM Length L Ch R = 1 ,5764.6  ,346.2,349.2,352.9
XS GIS Cut Line= 3
     2142544.113      217691.685      2142864.09      218400.603
     2142805.062      218904.075
#Sta/Elev= 30
       0 2288.13   176.5 2286.49   202.6 2287.72   297.4 2286.86   369.3 2285.21
     402 2282.54   418.3 2285.72   513.1 2283.69   517.1 2281.66   522.9 2280.02
     536 2281.73   568.6 2284.56   604.6  2283.2   617.6 2285.12   647.1 2285.91
   751.6  2286.4     817 2289.38   951.1 2298.96     974 2298.79  1026.3  2295.2
    1059 2297.27  1065.6 2296.32  1085.2 2297.71  1111.4  2297.4  1124.4  2299.2
  1134.3 2298.81    1167  2303.9    1216 2303.28  1248.7 2307.82  1284.7 2310.24
#Mann= 3 ,-1 , 0
       0     .12       0   517.1    .045       0     536     .12       0
#XS Ineff= 2 , 0
          419.67 2286.41  647.78         2286.48
Permanent Ineff=
       F       F
Bank Sta=517.1,536
XS Rating Curve= 0 ,0
Exp/Cntr=0.3,0.1

Type RM Length L Ch R = 1 ,5415.4  ,339.9,350,357.3
XS GIS Cut Line= 3
     2142286.563      217816.176     2142492.797      218361.096
     2142622.334      218886.063
#Sta/Elev= 30
       0 2286.87    32.7 2286.32    65.5 2283.91  204.122283.501   278.2    2283
   297.9 2283.76     324 2282.83   343.7 2283.64   379.7 2283.04   432.1 2280.48
   559.7 2282.54     563  2282.3   569.6 2278.47   575.1 2277.36   579.4 2277.18
   592.5 2277.37     622 2277.72   628.5 2280.37   638.4 2281.44   664.6 2281.06
   687.5  2279.4   713.7 2284.59   756.3 2303.55     776 2310.57   798.9 2316.34
   825.1  2321.5   864.5 2327.25  961.162336.646  1054.5 2341.82  1123.4 2343.64
#Mann= 5 ,-1 , 0
       0     .08       0  204.12     .12       0   575.1    .045       0
   592.5     .12       0  961.16     .06       0
Bank Sta=575.1,592.5
XS Rating Curve= 0 ,0
Exp/Cntr=0.3,0.1

Type RM Length L Ch R = 1 ,5065.4  ,340,348.3,355.8
XS GIS Cut Line= 3
     2142189.891       217832.77      2142161.93      218422.228
     2142117.677      218959.625
#Sta/Elev= 30
       0 2284.71   114.8 2281.77  156.912281.595   249.2 2280.16   311.4  2278.1
   331.1 2279.26   360.6 2278.35  383.122278.968   455.7 2276.94   485.2  2278.5
   563.9 2277.77   580.3 2274.66   583.6 2274.26   597.6 2274.66   606.5 2274.94
   632.6 2278.24   720.8 2281.64   737.2 2285.32   776.4 2298.04   792.7 2301.85
   822.2  2305.7   884.2 2308.15   910.4 2310.69   933.3 2314.66   969.2 2322.87
   995.4 2330.99  1041.1 2343.14    1077 2348.79 1112.242351.605  1129.3 2352.96
#Mann= 6 ,-1 , 0
       0     .12       0  156.91     .08       0  383.12     .12       0
   580.3    .045       0   597.6     .12       0 1112.24     .06       0
#XS Ineff= 2 , 0
          393.81 2281.62  635.29         2281.45
Permanent Ineff=
       F       F
Bank Sta=580.3,597.6
XS Rating Curve= 0 ,0
Exp/Cntr=0.3,0.1

Type RM Length L Ch R = 1 ,4717.1  ,283.1,285.2,286.1
XS GIS Cut Line= 2
     2142075.896      217806.853     2141612.354      218851.992
#Sta/Elev= 30
       0 2284.84   167.1 2280.41   314.5 2278.87   363.6 2275.86  468.012274.928
  472.72 2274.89     498 2274.35   507.8 2275.32   556.9 2276.28   573.3 2275.64
   583.1 2273.12   596.2 2271.93   599.5 2273.13   602.8 2274.41   622.4 2275.79
   655.2 2275.34   674.9 2276.34   796.1  2277.2   815.7  2281.4   832.1  2288.4
   858.3 2303.26   897.6 2323.14   936.9 2338.73   976.2 2347.98 1011.192353.362
  1051.6 2358.48  1087.6 2361.66    1104 2361.24  1117.1 2362.97  1143.3 2364.44
#Mann= 6 ,-1 , 0
       0     .12       0  468.01     .06       0  472.72     .12       0
   583.1    .045       0   599.5     .12       0 1011.19     .06       0
#XS Ineff= 2 , 0
          398.66 2279.36  733.94         2279.14
Permanent Ineff=
       F       F
Bank Sta=583.1,599.5
XS Rating Curve= 0 ,0
Exp/Cntr=0.3,0.1

Type RM Length L Ch R = 1 ,4431.8  ,576,600.3,599.4
XS GIS Cut Line= 2
     2141871.034       217740.88     2141402.284      218775.603
#Sta/Elev= 30
       0 2283.41    65.5 2281.31   386.3 2274.84   451.8 2275.55   487.8 2272.58
     514 2273.46   523.8 2272.92   533.6  2274.2     550 2273.31   559.8  2274.2
   569.6 2271.58   579.4 2270.38     586 2271.48   618.7 2274.06   625.3 2275.56
   703.8 2274.62   749.7 2275.58   772.6 2284.48   828.2 2313.74   854.4 2326.33
   877.3 2335.93   913.3  2343.6  940.092347.261   959.2 2350.09   991.9  2352.9
    1005 2352.34  1021.4  2353.4  1057.4 2353.63  1073.8 2352.43    1136 2351.01
#Mann= 4 ,-1 , 0
       0     .12       0   569.6    .045       0     586     .12       0
  940.09     .06       0
Bank Sta=569.6,586
XS Rating Curve= 0 ,0
Exp/Cntr=0.3,0.1

Type RM Length L Ch R = 1 ,3831.5  ,333.7,352.9,352.1
XS GIS Cut Line= 2
     2141522.076       217584.63      2141207.84      218621.089
#Sta/Elev= 30
       0 2286.63    16.4 2281.09    52.4 2278.56   150.5 2276.33   363.2 2274.86
   379.6 2273.37   395.9 2274.04   418.8 2272.63   451.5 2272.28   467.9 2269.51
   477.7 2268.21   487.5 2269.48   500.6 2268.81   523.5 2272.08   549.7 2270.91
   566.1 2271.47   595.5 2270.71   621.7 2273.12   657.7 2272.87   687.1 2271.13
   719.8 2271.38   768.9 2274.25   791.8 2278.67     818 2289.82   844.2 2302.59
   883.4 2317.66  938.222331.152  1004.5  2341.1  1060.1 2341.32    1083 2339.27
#Mann= 4 ,-1 , 0
       0     .12       0   467.9    .045       0   487.5     .12       0
  938.22     .06       0
#XS Ineff= 2 , 0
          396.72 2275.07
Permanent Ineff=
       F       F
Bank Sta=467.9,487.5
XS Rating Curve= 0 ,0
Exp/Cntr=0.3,0.1

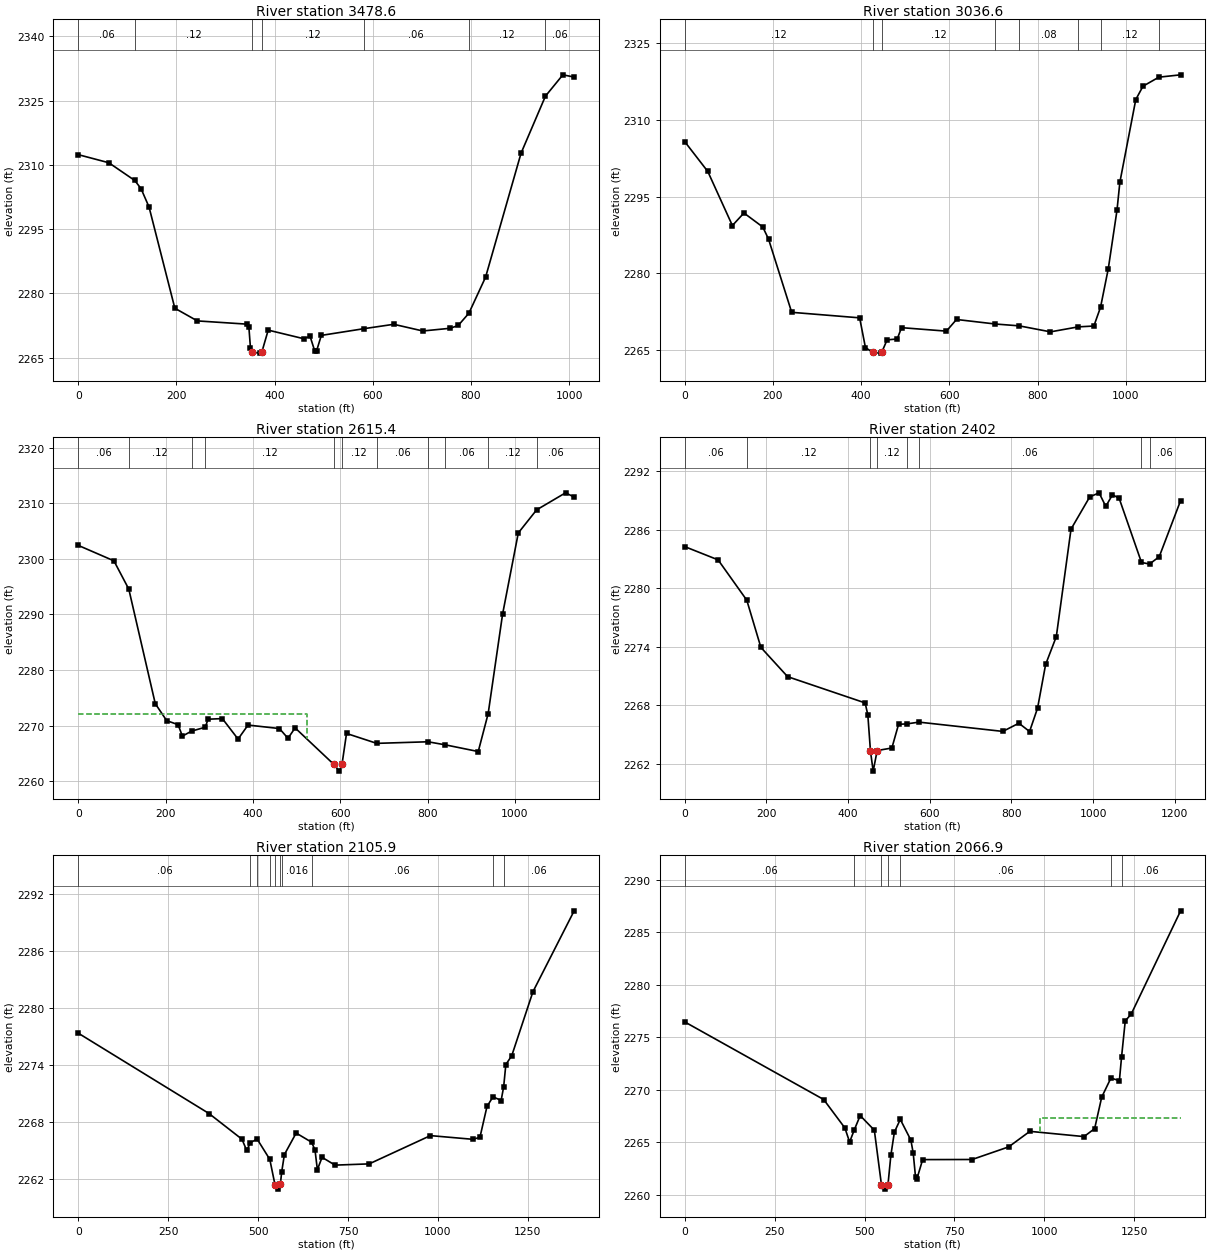
Type RM Length L Ch R = 1 ,3478.6  ,445.8,442,435.2
XS GIS Cut Line= 2
     2141296.382        217544.7     2140971.729      218501.297
#Sta/Elev= 30
       0 2312.37    62.3 2310.48  115.112306.346   127.9 2304.45   144.3 2300.14
   196.8 2276.52   242.7 2273.56   344.4  2272.8   347.7 2272.03   350.9 2267.16
   354.4 2266.25   370.6 2266.04   373.9 2266.24     387 2271.41   459.2 2269.41
   472.3 2269.96   482.1 2266.43   485.4 2266.52   495.2 2270.18   581.6 2271.74
   642.8 2272.77   701.9 2271.21   757.6 2271.84     774 2272.49  795.752275.351
   829.8 2283.78     902  2312.7  951.752326.029   987.2    2331  1010.2 2330.48
#Mann= 7 ,-1 , 0
       0     .06       0  115.11     .12       0   354.4    .045       0
   373.9     .12       0   581.6     .06       0  795.75     .12       0
  951.75     .06       0
Bank Sta=354.4,373.9
XS Rating Curve= 0 ,0
Exp/Cntr=0.3,0.1

Type RM Length L Ch R = 1 ,3036.6  ,426.4,421.2,408.9
XS GIS Cut Line= 2
     2140931.798      217355.464     2140787.701      218470.047
#Sta/Elev= 30
       0 2305.77    52.4 2299.92   108.1 2289.35   134.3  2291.8   176.9 2289.07
     190 2286.71   242.5 2272.38   396.5  2271.3   409.6  2265.5     426 2264.53
   445.6  2264.4  446.532264.552   458.7 2266.99   481.6 2267.17   491.5 2269.38
   593.1  2268.7     616 2270.98   704.32270.091  757.942269.735     829 2268.56
  891.692269.532   927.3  2269.7  942.45 2273.38     960 2280.92   979.7 2292.33
   986.2 2297.81  1022.3 2313.99  1038.7  2316.6  1074.6 2318.36  1123.9 2318.82
#Mann= 8 ,-1 , 0
       0     .12       0     426    .045       0  446.53     .12       0
   704.3     .06       0  757.94     .08       0  891.69     .06       0
  942.45     .12       0  1074.6     .06       0
Bank Sta=426,446.53
XS Rating Curve= 0 ,0
Exp/Cntr=0.3,0.1

Type RM Length L Ch R = 1 ,2615.4  ,214.5,213.4,214.7
XS GIS Cut Line= 3
     2140503.667      217314.568     2140544.894       217911.08
      2140653.84      218437.445
#Sta/Elev= 30
       0 2302.42    81.7 2299.64  115.812294.558   176.4 2273.98   202.6 2270.92
   228.7  2270.2   238.5 2268.14  259.462269.037  290.882269.741   297.3 2271.18
     330 2271.29     366 2267.61   388.8 2270.13   460.7  2269.5   480.3 2267.75
   496.6 2269.62  585.162263.068   597.9 2261.85  603.962263.052   614.3 2268.62
  683.532266.839  800.812267.125  840.612266.571   915.9 2265.37  938.652272.196
   971.6 2290.04  1007.6 2304.65 1049.562308.798  1115.8 2311.86  1135.5  2311.1
#Mann= 11 ,-1 , 0
       0     .06       0  115.81     .12       0  259.46     .04       0
  290.88     .12       0  585.16    .045       0  603.96     .12       0
  683.53     .06       0  800.81     .08       0  840.61     .06       0
  938.65     .12       0 1049.56     .06       0
#XS Ineff= 2 , 0
          524.23 2272.06
Permanent Ineff=
       F       F
Bank Sta=585.16,603.96
XS Rating Curve= 0 ,0
Exp/Cntr=0.3,0.1

Type RM Length L Ch R = 1 ,2402    ,293.8,296.1,298.1
XS GIS Cut Line= 2
     2140291.367       217386.89     2140444.145      218591.751
#Sta/Elev= 30
       0 2284.27    81.8 2282.91  152.072278.779   186.6 2273.94   252.1 2270.94
   441.9 2268.25   448.5 2267.03     455 2263.29   461.6 2261.26   471.4 2263.37
   507.4 2263.63   523.8 2266.06  543.912266.099  573.692266.282   779.1 2265.33
   818.4 2266.17   844.6 2265.32   864.2 2267.72   883.9 2272.19   910.1 2275.05
   946.1 2286.06   991.9 2289.36  1014.8 2289.78  1031.2 2288.39  1047.6 2289.58
  1063.9 2289.23 1118.692282.643 1138.392282.485  1162.1 2283.23  1214.5 2288.99
#Mann= 8 ,-1 , 0
       0     .06       0  152.07     .12       0     455    .045       0
   471.4     .12       0  543.91     .08       0  573.69     .06       0
 1118.69     .12       0 1138.39     .06       0
Bank Sta=455,471.4
XS Rating Curve= 0 ,0
Exp/Cntr=0.3,0.1

Type RM Length L Ch R = 1 ,2105.9  ,39.1,39,39.1
XS GIS Cut Line= 2
     2140058.173      217394.165     2140099.405      218772.203
#Sta/Elev= 30
       0 2277.37   363.5  2268.9   455.2 2266.19   468.3 2265.01  478.872265.832
  497.332266.207  532.542264.068     547 2261.39   556.7 2260.93     562 2261.45
  565.492262.708   573.1 2264.57   605.8 2266.84  648.732265.875   658.2 2265.06
   664.8 2262.98   677.9 2264.28   713.9 2263.46   808.8 2263.59   979.1 2266.57
    1097 2266.18  1116.7 2266.39  1136.3 2269.64 1153.112270.663  1175.6 2270.27
 1182.662271.714  1188.7 2274.06  1205.1 2274.99    1264 2281.73  1378.6 2290.26
#Mann= 10 ,-1 , 0
       0     .06       0  478.87     .08       0  497.33     .06       0
  532.54     .12       0     547    .045       0     562     .12       0
  565.49    .016       0  648.73     .06       0 1153.11     .08       0
 1182.66     .06       0
Bank Sta=547,562
XS Rating Curve= 0 ,0
Exp/Cntr=0.3,0.1

Type RM Length L Ch R = 1 ,2066.9  ,403.9,399,393.2
XS GIS Cut Line= 2
      2140019.11      217391.994     2140060.343      218770.033
#Sta/Elev= 30
       0 2276.47   386.4 2269.08   445.4 2266.37   458.5 2265.03  471.18 2266.17
   487.9 2267.55   527.2 2266.16   546.9 2260.98   556.7 2260.55  565.182260.988
   573.1 2263.76   582.9 2265.97  599.332267.189   628.8 2265.21   635.3 2263.97
   641.8 2261.67   645.1 2261.48   661.5 2263.36     799 2263.37   900.6 2264.57
   959.5 2266.05  1110.1 2265.55  1139.6 2266.31  1159.2  2269.3 1184.832271.124
  1208.4 2270.87 1214.382273.115  1224.7 2276.57  1241.1  2277.2  1378.6 2287.04
#Mann= 7 ,-1 , 0
       0     .06       0  471.18    .016       0   546.9    .045       0
  565.18    .016       0  599.33     .06       0 1184.83     .08       0
 1214.38     .06       0
#XS Ineff= 2 , 0
                          988.24          2267.3
Permanent Ineff=
       F       F
Bank Sta=546.9,565.18
XS Rating Curve= 0 ,0
Exp/Cntr=0.3,0.1

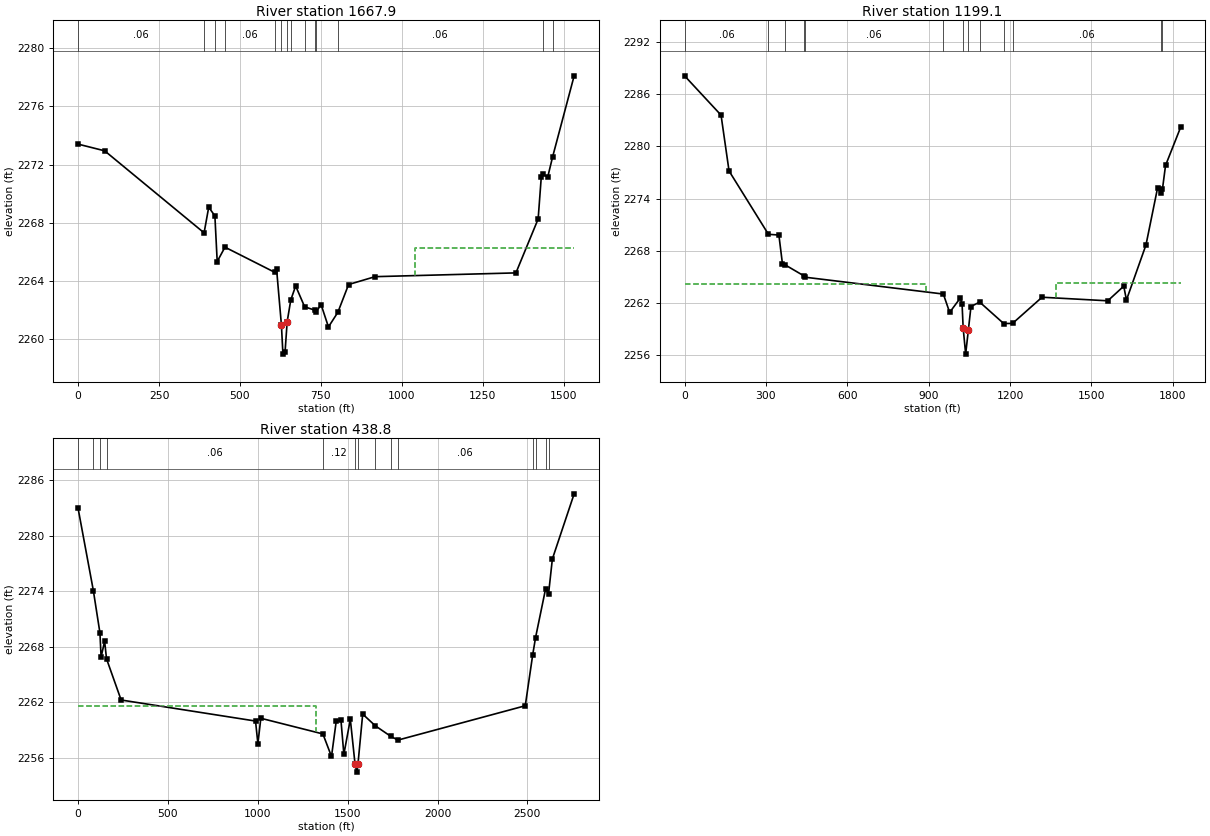
Type RM Length L Ch R = 1 ,1667.9  ,469.8,468.8,464.4
XS GIS Cut Line= 3
     2139770.534      217348.696     2139610.812       217824.39
     2139885.117      218817.446
#Sta/Elev= 30
       0 2273.41      82 2272.95  389.132267.305   403.4 2269.07  422.482268.471
   429.6 2265.33  453.63 2266.32  607.772264.585     613 2264.81  627.932260.966
   632.6 2258.96   639.2 2259.11   645.7 2261.19  656.89 2262.69   671.9 2263.65
  699.58 2262.22  731.022261.983  734.122261.833   750.4 2262.37   773.2 2260.83
  802.252261.838   835.4 2263.75   917.2 2264.29  1352.2 2264.55  1420.8 2268.26
  1430.6 2271.18 1435.052271.354  1450.3 2271.14  1465.72272.551    1532 2278.11
#Mann= 14 ,-1 , 0
       0     .06       0  389.13    .016       0  422.48     .08       0
  453.63     .06       0  607.77     .12       0  627.93    .045       0
   645.7     .12       0  656.89     .06       0  699.58     .12       0
  731.02     .06       0  734.12     .12       0  802.25     .06       0
 1435.05     .08       0  1465.7     .06       0
#XS Ineff= 2 , 0
                         1040.25         2266.23
Permanent Ineff=
       F       F
Bank Sta=627.93,645.7
XS Rating Curve= 0 ,0
Exp/Cntr=0.3,0.1

Type RM Length L Ch R = 1 ,1199.1  ,753.9,760.4,755.5
XS GIS Cut Line= 3
     2139358.882      217176.644     2139226.937      217992.617
     2139647.076      218902.339
#Sta/Elev= 30
       0 2288.09   134.5 2283.58     164 2277.17  309.18  2269.9   347.7 2269.82
   360.8 2266.52  370.782266.393  439.282265.144  444.442264.978  953.942263.045
   977.2 2260.94  1016.5 2262.59    1023 2261.89 1027.032259.142  1036.2 2256.15
    1046 2258.87  1055.8 2261.61 1087.752262.127  1176.62259.656 1209.132259.677
  1317.8 2262.68  1560.1 2262.27    1619 2263.95  1628.9 2262.36  1700.9 2268.68
  1743.5  2275.2 1757.532274.632 1761.572275.061    1773  2277.8  1828.6 2282.18
#Mann= 13 ,-1 , 0
       0     .06       0  309.18    .016       0  370.78     .06       0
  439.28     .12       0  444.44     .06       0  953.94     .12       0
 1027.03    .045       0    1046     .12       0 1087.75     .06       0
  1176.6     .12       0 1209.13     .06       0 1757.53     .08       0
 1761.57     .06       0
#XS Ineff= 2 , 0
          889.58 2264.16 1370.48         2264.28
Permanent Ineff=
       F       F
Bank Sta=1027.03,1046
XS Rating Curve= 0 ,0
Exp/Cntr=0.3,0.1

Type RM Length L Ch R = 1 ,438.8   ,438,438.8,433.5
XS GIS Cut Line= 4
     2139299.854      217141.922     2138518.604      217718.311
     2138782.493      218603.728     2139567.215      218968.311
#Sta/Elev= 30
       0 2282.93   84.852274.067  121.562269.495   127.9 2266.89   147.6  2268.6
  158.272266.699   239.4 2262.26   987.2 2259.99  1000.4 2257.55  1016.7 2260.29
 1362.062258.599  1409.9 2256.17  1436.1 2259.95  1462.3 2260.14  1478.7  2256.4
  1514.7 2260.18  1540.9 2255.35  1550.8 2254.48  1557.3 2255.37  1583.5 2260.74
 1653.662259.478 1738.662258.354 1779.452257.936    2488 2261.64 2529.392267.132
 2545.172268.984 2600.672274.208  2617.82273.744  2638.8 2277.47    2760  2284.5
#Mann= 14 ,-1 , 0
       0     .06       0   84.85     .08       0  121.56    .016       0
  158.27     .06       0 1362.06     .12       0  1540.9    .045       0
  1557.3     .12       0 1653.66     .06       0 1738.66     .12       0
 1779.45     .06       0 2529.39     .12       0 2545.17     .06       0
 2600.67     .08       0  2617.8     .06       0
#XS Ineff= 2 , 0
         1321.98 2261.59
Permanent Ineff=
       F       F
Bank Sta=1540.9,1557.3
XS Rating Curve= 0 ,0
Exp/Cntr=0.3,0.1

Chan Stop Cuts=-1
Use User Specified Reach Order=0
Composite Channel Slope=5